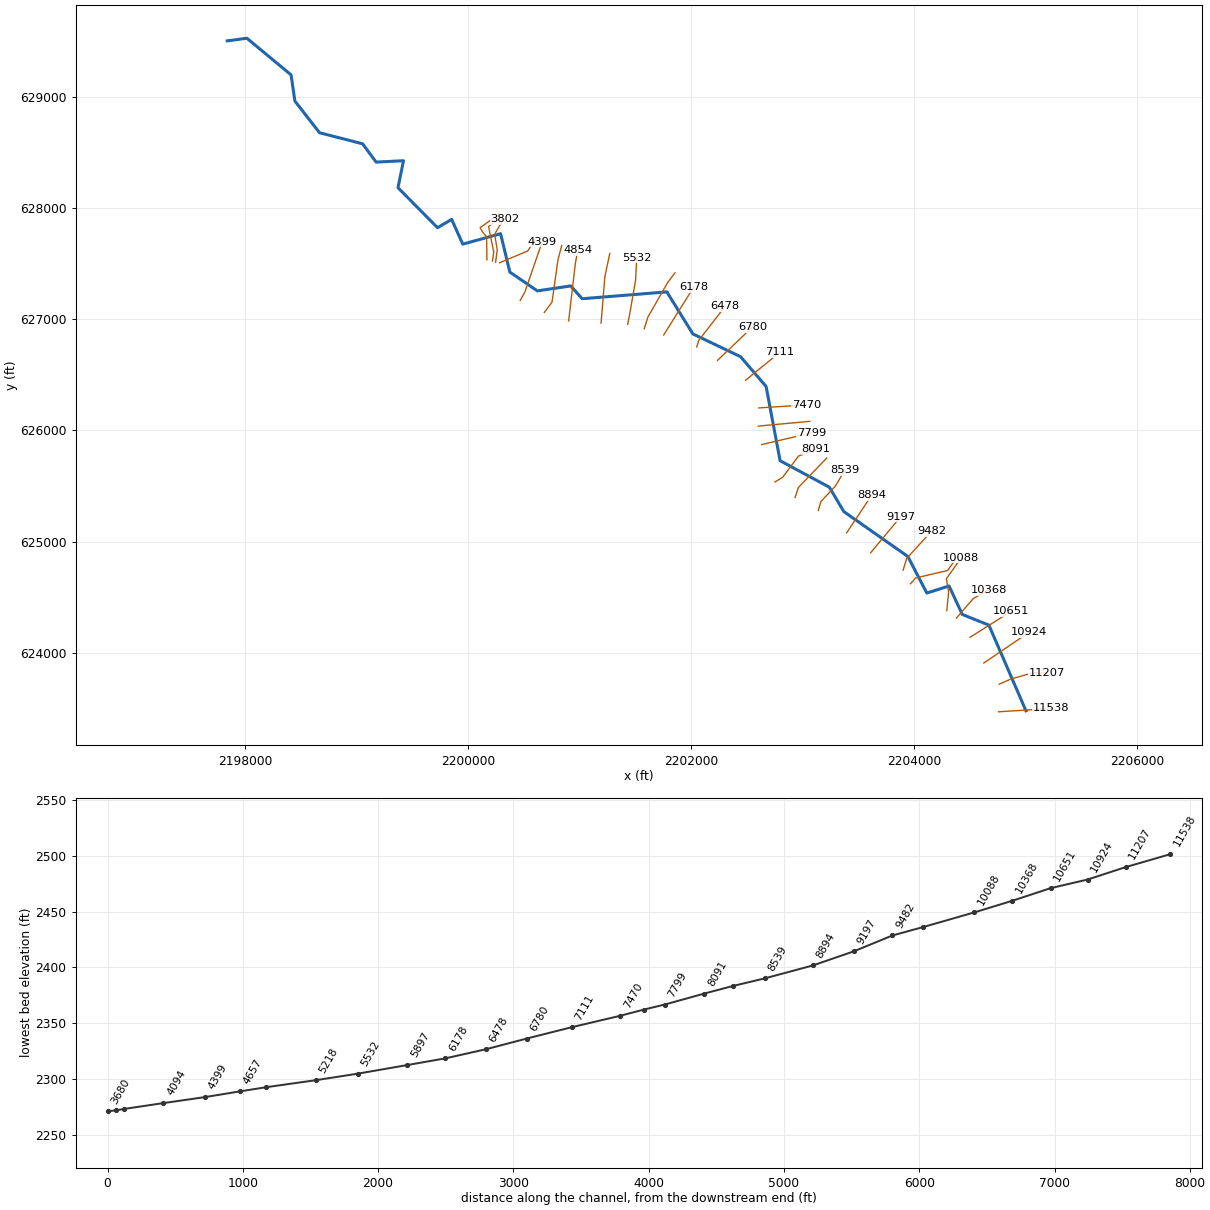
--- TROUTRN.prj (project) ---

Proj Title=TROUTRN
Current Plan=p01
Default Exp/Contr=0,0
English Units
Geom File=g01
Flow File=f01
Plan File=p01
BEGIN DESCRIPTION:
----------MODEL BY WOOD PLC 2022----------
AFH study
Randolph County, WV
HEC-RAS Version: RAS 6.2
Vertical Datum: NAVD88
Projection: NAD 1983 StatePlane West Virginia S FIPS 4702 (US Feet)
Terrain: 1-meter LIDAR (FEMA Region III 3DEP collected 2016-2018)
Land Use: 2019 NLCD
Hydrologic Method:
WV SIR2010-5033 regression equations
Additional Model Notes:
None
END DESCRIPTION:
DSS File=dss
DSS Export Rating Curves= 0
DSS Export Rating Curve Sorted= 0
DSS Export Volume Flow Curves= 0
DXF OffsetX= 0
DXF OffsetY= 0
DXF ScaleX= 0
DXF ScaleY= 0

--- TROUTRN.p01 (plan) ---

Plan Title=Floodplain
Program Version=6.20
Short Identifier=Floodplain
Geom File=g01
Flow File=f01
Subcritical Flow
K Sum by GR= 0
Std Step Tol= 0.01
Critical Tol= 0.01
Num of Std Step Trials= 20
Max Error Tol= 0.3
Flow Tol Ratio= 0.001
Split Flow NTrial= 30
Split Flow Tol= 0.02
Split Flow Ratio= 0.02
Log Output Level= 0
Friction Slope Method= 1
Unsteady Friction Slope Method= 2
Unsteady Bridges Friction Slope Method= 1
Parabolic Critical Depth
Global Vel Dist= 0 , 0 , 0
Global Log Level= 0
CheckData=True
Encroach Param=-1 ,0,0, 0
Computation Interval=0.1SEC
Output Interval=1SEC
Instantaneous Interval=Max Profile
Mapping Interval=1HOUR
Computation Time Step Use Courant=        0
Computation Time Step Use Time Series=    0
Computation Time Step Count To Double=0
Computation Time Step Max Doubling=0
Computation Time Step Max Halving=0
Computation Time Step Residence Courant=0
Run HTab= 0
Run UNet= 0
Run Sediment= 0
Run PostProcess= 0
Run WQNet= 0
Run RASMapper=-1
UNET Theta= 0
UNET Theta Warmup= 0
UNET ZTol= 0
UNET ZSATol= 0
UNET MxIter= 0
UNET Max Iter WO Improvement= 0
UNET MaxInSteps= 0
UNET DtIC= 0
UNET DtMin= 0
UNET MaxCRTS= 0
UNET WFStab= 0
UNET SFStab= 0
UNET WFX= 1
UNET SFX= 1
UNET Gravity=32.174
UNET 1D Methodology=Finite Difference
UNET DSS MLevel= 1
UNET Pardiso=0
UNET DZMax Abort= 0
UNET Use Existing IB Tables= 0
UNET Froude Reduction=False
UNET Froude Limit= 0
UNET Froude Power= 0
UNET D1 Cores= 0
UNET WindReference=Eulerian
UNET WindDragFormulation=Hsu (1988)
UNET D2 Coriolis=0
UNET D2 Cores= 0
UNET D2 Theta= 1
UNET D2 Theta Warmup= 1
UNET D2 Z Tol= 0.01
UNET D2 Volume Tol= 0.01
UNET D2 Max Iterations= 20
UNET D2 Equation= 0
UNET D2 RampUpFraction=0.1
UNET D2 TimeSlices= 1
UNET D2 Turbulence Formulation=Non-Conservative (original)
UNET D2 Eddy Viscosity=0.3
UNET D2 Transverse Eddy Viscosity=0.1
UNET D2 Smagorinsky Mixing=0
UNET D2 BCVolumeCheck=0
UNET D2 Cores=0
UNET D2 SolverType=PARDISO (Direct)
UNET D2 Minimum Iterations= 2147483647
UNET D2 Maximum Iterations= 2147483647
UNET D2 Restart Number= 10
UNET D2 Relaxation Coeff=1.3
UNET D2 SOR Precondition Iterations= 10
UNET D2 ILUT Maximum Fill= 8
UNET D2 ILUT Tolerance=1E-08
UNET D1D2 MaxIter= 0
UNET D1D2 ZTol=0.01
UNET D1D2 QTol=0.1
UNET D1D2 MinQTol=1
DSS File=dss
Write IC File= 0
Write IC File at Fixed DateTime=0
Write IC File at Sim End=0
Echo Input=False
Echo Parameters=False
Echo Output=False
Write Detailed= 0
HDF Write Warmup=0
HDF Write Time Slices=0
HDF Flush=0
HDF Compression= 1
HDF Chunk Size= 1
HDF Spatial Parts= 1
HDF Use Max Rows=0
HDF Fixed Rows= 1
Calibration Method= 0
Calibration Iterations= 20
Calibration Max Change=0.05
Calibration Tolerance=0.2
Calibration Maximum=1.5
Calibration Minimum=0.5
Calibration Optimization Method= 1
WQ AD Non Conservative
WQ ULTIMATE=-1
WQ Max Comp Step=1HOUR
WQ Output Interval=15MIN
WQ Output Selected Increments= 0
WQ Output face flow=0
WQ Output face velocity=0
WQ Output face area=0
WQ Output face dispersion=0
WQ Output cell volume=0
WQ Output cell surface area=0
WQ Output cell continuity=0
WQ Output cumulative cell continuity=0
WQ Output face conc=0
WQ Output face dconc_dx=0
WQ Output face courant=0
WQ Output face peclet=0
WQ Output face adv mass=0
WQ Output face disp mass=0
WQ Output cell mass=0
WQ Output cell source sink temp=0
WQ Output nsm pathways=0
WQ Output nsm derived pathways=0
WQ Create Restart=0
WQ Fixed Restart=0
WQ System Summary=0
WQ Write To DSS=0
Sorting and Armoring Iterations= 10
XS Update Threshold= 0.02
Bed Roughness Predictor= 0
Hydraulics Update Threshold= 0.02
Energy Slope Method= 1
Volume Change Method= 1
Sediment Retention Method= 0
Sediment TS Multiplier= 1
Warm Up Method= 0
XS Weighting Method= 0
Number of US Weighted Cross Sections= 1
Number of DS Weighted Cross Sections= 1
Upstream XS Weight=0
Main XS Weight=1
Downstream XS Weight=0
Number of DS XS's Weighted with US Boundary= 1
Upstream Boundary Weight= 1
Weight of XSs Associated with US Boundary= 0
Number of US XS's Weighted with DS Boundary= 1
Downstream Boundary Weight= 0.5
Weight of XSs Associated with DS Boundary= 0.5
Percentile Method= 0
Sediment Output Level= 3
Mass or Volume Output= 0
Output Increment Type= 1
Profile and TS Output Increment= 1
Transport Output Increment 1
XS Output Flag= 0
XS Output Increment= 10
Read HDF5 Sediment Hotstart= 0
Sediment Hotstart Type= 0
Write Gradation File= 0
Read Gradation Hotstart= 0
Write HDF5 File= 1
Write Binary Output= 1
Write DSS Sediment File= 0
DSS Sediment Output Type= 1
SV Curve= 0
Specific Gage Flag= 0
Subcell Erosion Methods= 0
Subcell Deposition Methods= 0
Advection Scheme= 1
Matrix Solver= 0
Implicit Weighting Factor= 1
Maximum Outer Loop Convergence Iterations= 5
Convergence Maximum Absolute= 0.001
Convergence RMSE= 0.0001
Grain Fractions Max Abs Error= 0.001
Max Subgrid Regions= 1
Max Subgrid Length Scale= 3.402823E+38
Initial Layer Thickness= 3.402823E+38
Min Layer Thickness= 3.402823E+38
Max Layer Thickness= 3.402823E+38
Number of Layers= 5

--- TROUTRN.f01 (steady flow) ---

Flow Title=Flow
Program Version=6.20
Number of Profiles= 1
Profile Names=P100yr
River Rch & RM=TROUTRN,Main            ,11538
     398
River Rch & RM=TROUTRN,Main            ,8091
     454
River Rch & RM=TROUTRN,Main            ,4854
     511
River Rch & RM=TROUTRN,Main            ,4094
     569
Boundary for River Rch & Prof#=TROUTRN,Main            , 1
Up Type= 0
Dn Type= 3
Dn Slope=0.03184
DSS Import GetInterval= 0
DSS Import GetPeak= 0
DSS Import FillOption= 0

--- TROUTRN.g01 (geometry) ---

Geom Title=Geometry
Program Version=6.20

River Reach=TROUTRN         ,Main
Reach XY= 30
     2205005.015      623481.576      2204672.55      624251.541
     2204433.835      624347.461     2204315.271      624603.115
     2204115.692      624539.301     2203945.554       624867.86
     2203370.901      625271.506     2203240.693       625490.69
2202799.26875816625728.4680109452202673.63016445626395.183564277
     2202444.252      626663.043     2202016.821      626867.209
2201782.99497602627245.2067904062201023.64904059627183.745594097
2200920.63139836627298.773968075     2200620.858      627254.353
     2200374.503      627423.103      2200291.17      627767.895
     2199951.639      627674.217     2199852.305      627896.626
2199725.28629552627821.963633425     2199370.675       628181.44
 2199420.0785816628423.633920526     2199174.244      628411.331
     2199053.249      628575.738     2198666.845      628674.908
     2198445.931      628959.3052198411.01131978629195.251299445
     2198015.033      629523.922     2197837.641      629500.324

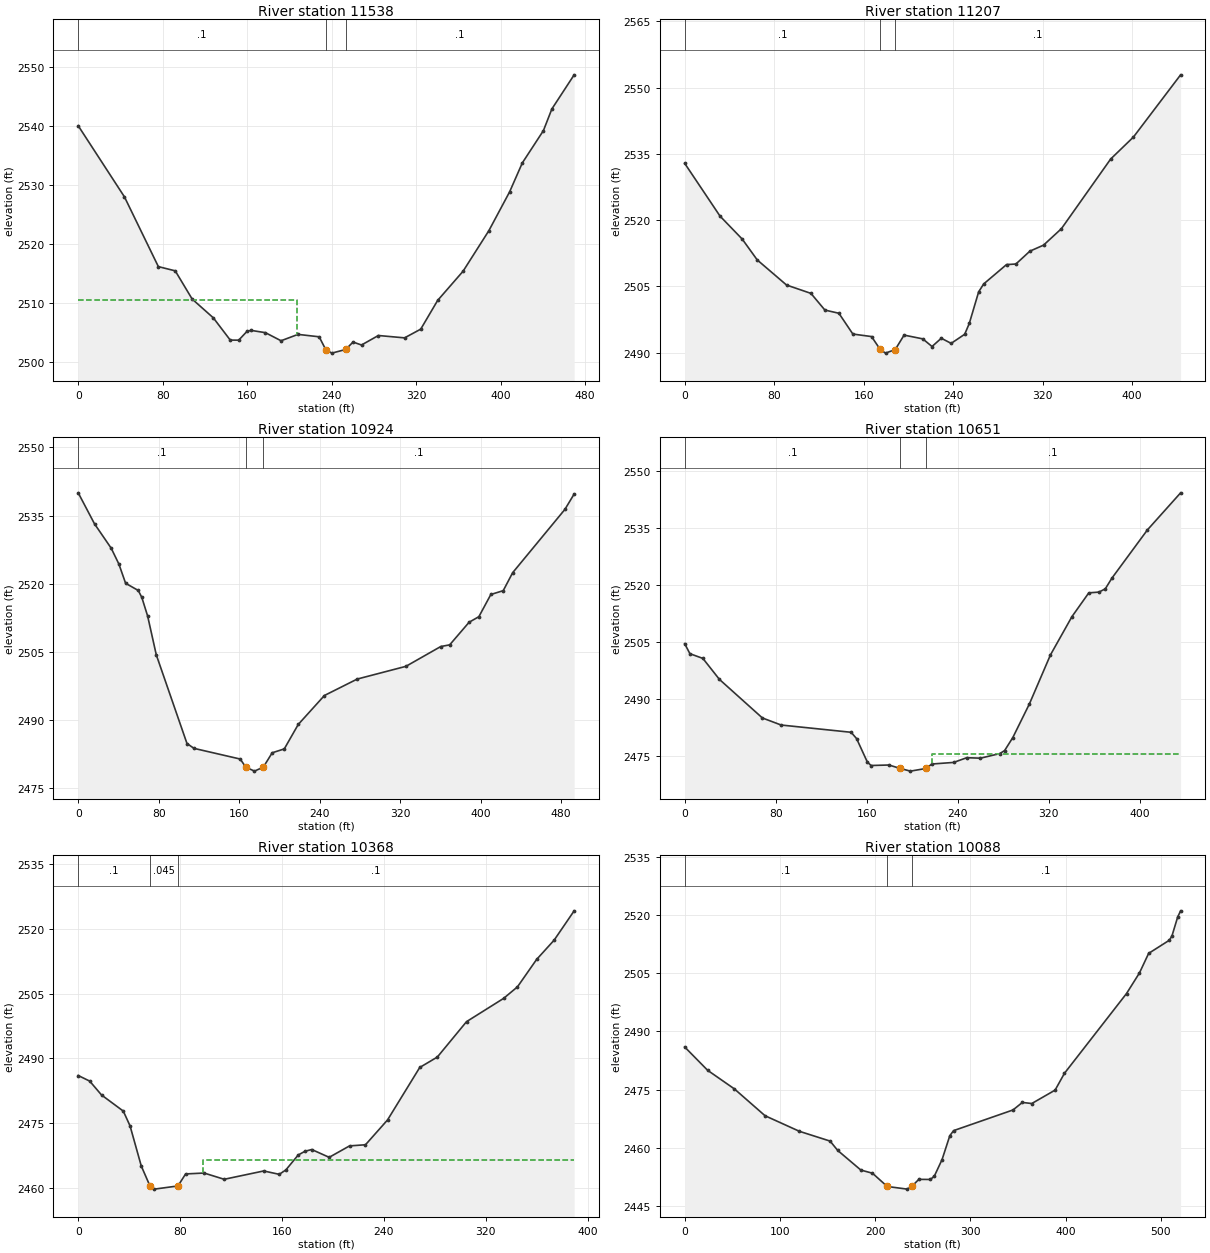
Type RM Length L Ch R = 1 ,11538   ,327.2,330.8,332
XS GIS Cut Line= 2
2204760.44831399623472.6266348912205229.17645462623502.723741859
#Sta/Elev= 30
       0 2540.11    43.8 2528.04    75.9 2516.21    91.9 2515.49   107.9 2510.71
     128 2507.51     144 2503.74     152 2503.73   160.1 2505.27   164.1 2505.38
   177.3    2505   192.1 2503.63   208.2 2504.71   228.2  2504.3   234.42502.138
   240.2 2501.53   253.32502.148   260.3 2503.41   268.3 2502.91   284.3 2504.52
   309.1 2504.12   324.4  2505.6   340.4 2510.47   364.5 2515.43   388.9  2522.3
   408.6  2528.9   420.6  2533.8   440.6 2539.29   448.6 2542.96   469.7 2548.75
#Mann= 3 ,-1,0
       0      .1       0   234.4    .045       0   253.3      .1       0
#XS Ineff= 2 , 0
          207.49 2510.54
Permanent Ineff=
       F       F
Bank Sta=234.4,253.3
XS Rating Curve= 0 ,0
Exp/Cntr=0.3,0.1

Type RM Length L Ch R = 1 ,11207   ,279.6,282.3,283.6
XS GIS Cut Line= 4
2204764.79692472623720.4386039762204867.91053869623765.857695843
2205063.08987942623822.3246749222205190.75435386623821.097131898
#Sta/Elev= 30
       0 2532.87    31.6 2520.92    51.5  2515.7    64.9 2510.99    91.1 2505.31
   112.9 2503.42   125.4 2499.64   137.9 2498.92   150.4 2494.21   167.1 2493.64
   174.82490.742   179.6 2489.89   188.3  2490.7   196.2 2493.97   212.9 2493.12
   221.2 2491.39   229.5 2493.26   238.3  2492.1   250.4 2494.16   254.5  2496.6
   262.9 2503.77   267.4 2505.56   287.8 2509.94   296.2 2510.07   308.7 2512.98
   320.9 2514.34   336.9 2518.07   380.9 2533.83   401.3 2538.82   443.5 2552.91
#Mann= 3 ,-1,0
       0      .1       0   174.8    .045       0   188.3      .1       0
Bank Sta=174.8,188.3
XS Rating Curve= 0 ,0
Exp/Cntr(USF)=0,0
Exp/Cntr=0.3,0.1

Type RM Length L Ch R = 1 ,10924   ,273.4,273.8,273.9
XS GIS Cut Line= 2
2204626.77367909623910.727551205  2205034.524493624187.711655812
#Sta/Elev= 30
       0    2540    16.2 2533.17    32.8  2527.8    40.4 2524.33    47.1 2520.09
    59.7  2518.5    63.2 2516.98      69 2512.87    77.6 2504.33   108.1 2484.81
   115.1 2483.74     161 2481.39   166.62479.595   175.2 2478.73     1842479.613
   192.8 2482.77   204.8 2483.62   218.7 2489.01   244.7 2495.38   277.3    2499
   325.7  2501.8   360.3 2506.16   369.2 2506.53   388.5 2511.51   398.2 2512.73
   410.1 2517.62   422.4 2518.46   431.8 2522.42   483.7 2536.35   492.9 2539.74
#Mann= 3 ,-1,0
       0      .1       0   166.6    .045       0     184      .1       0
Bank Sta=166.6,184
XS Rating Curve= 0 ,0
Exp/Cntr=0.3,0.1

Type RM Length L Ch R = 1 ,10651   ,278.7,283,285.5
XS GIS Cut Line= 2
2204504.55780375624142.7134040412204872.82071078624375.946578496
#Sta/Elev= 30
       0 2504.53     4.6 2501.89      16 2500.65    30.5 2495.14    68.3 2484.98
    84.8 2483.12   146.3 2481.21   151.1 2479.55   160.5 2473.41   163.8 2472.47
   179.5  2472.6   189.62471.682   198.4 2470.99     2122471.684   217.3 2472.86
   236.4 2473.28   247.9 2474.52     260  2474.4   276.9  2475.6   281.2  2476.4
   288.4 2479.82     303 2488.68   321.5 2501.58   340.4 2511.65   355.2  2517.9
   364.1  2518.1   369.7 2518.96   375.5 2521.77   406.7 2534.46   435.9 2544.22
#Mann= 3 ,-1,0
       0      .1       0   189.6    .045       0     212      .1       0
#XS Ineff= 2 , 0
                          217.69         2475.56
Permanent Ineff=
       F       F
Bank Sta=189.6,212
XS Rating Curve= 0 ,0
Exp/Cntr(USF)=0,0
Exp/Cntr=0.3,0.1

Type RM Length L Ch R = 1 ,10368   ,266.5,279.6,290.4
XS GIS Cut Line= 3
2204381.12707095624314.3656547142204532.32379534624489.802426775
2204669.84638021624566.952869749
#Sta/Elev= 30
       0 2486.01       9 2484.72    18.3  2481.5    35.4 2477.76    40.7 2474.33
    49.5 2465.04    56.32460.428    59.8 2459.68    78.32460.419    84.3  2463.2
    98.8 2463.41   114.6 2461.96   145.6 2463.89   157.8 2463.11     163 2464.13
   172.7 2467.59     178 2468.45   183.3 2468.86     197 2467.05     213  2469.7
   225.5 2469.96   242.8 2475.71   268.1 2487.88   281.9 2490.29   304.8 2498.49
   333.9 2503.88   344.8 2506.56   359.8  2512.9   373.6 2517.39   389.3 2524.18
#Mann= 3 ,-1,0
       0      .1       0    56.3    .045       0    78.3      .1       0
#XS Ineff= 2 , 0
                           98.19         2466.33
Permanent Ineff=
       F       F
Bank Sta=56.3,78.3
XS Rating Curve= 0 ,0
Exp/Cntr=0.3,0.1

Type RM Length L Ch R = 1 ,10088   ,392.6,378.8,361.5
XS GIS Cut Line= 4
2204294.80514771624381.2358953922204311.60072094624549.305768601
2204290.96531767624668.1018180762204425.10625814624856.528519741
#Sta/Elev= 30
       0 2485.98    24.1 2479.96    52.2 2475.16    84.4 2468.24   120.5 2464.22
   152.7  2461.7   160.7 2459.29     185 2454.23   197.2 2453.41   212.72449.993
   233.7 2449.31   238.42450.001   245.9 2451.83   258.1  2451.8   262.2 2452.68
   270.3 2456.94   278.4 2463.07   282.4  2464.4   344.8 2469.73   354.6 2471.67
   364.5 2471.39     389 2474.85   398.8 2479.18     464 2499.76   477.6 2505.08
   487.2 2510.11   509.1 2513.53   511.8 2514.69   517.7 2519.49   520.8 2521.09
#Mann= 3 ,-1,0
       0      .1       0   212.7    .045       0   238.4      .1       0
Bank Sta=212.7,238.4
XS Rating Curve= 0 ,0
Exp/Cntr=0.3,0.1

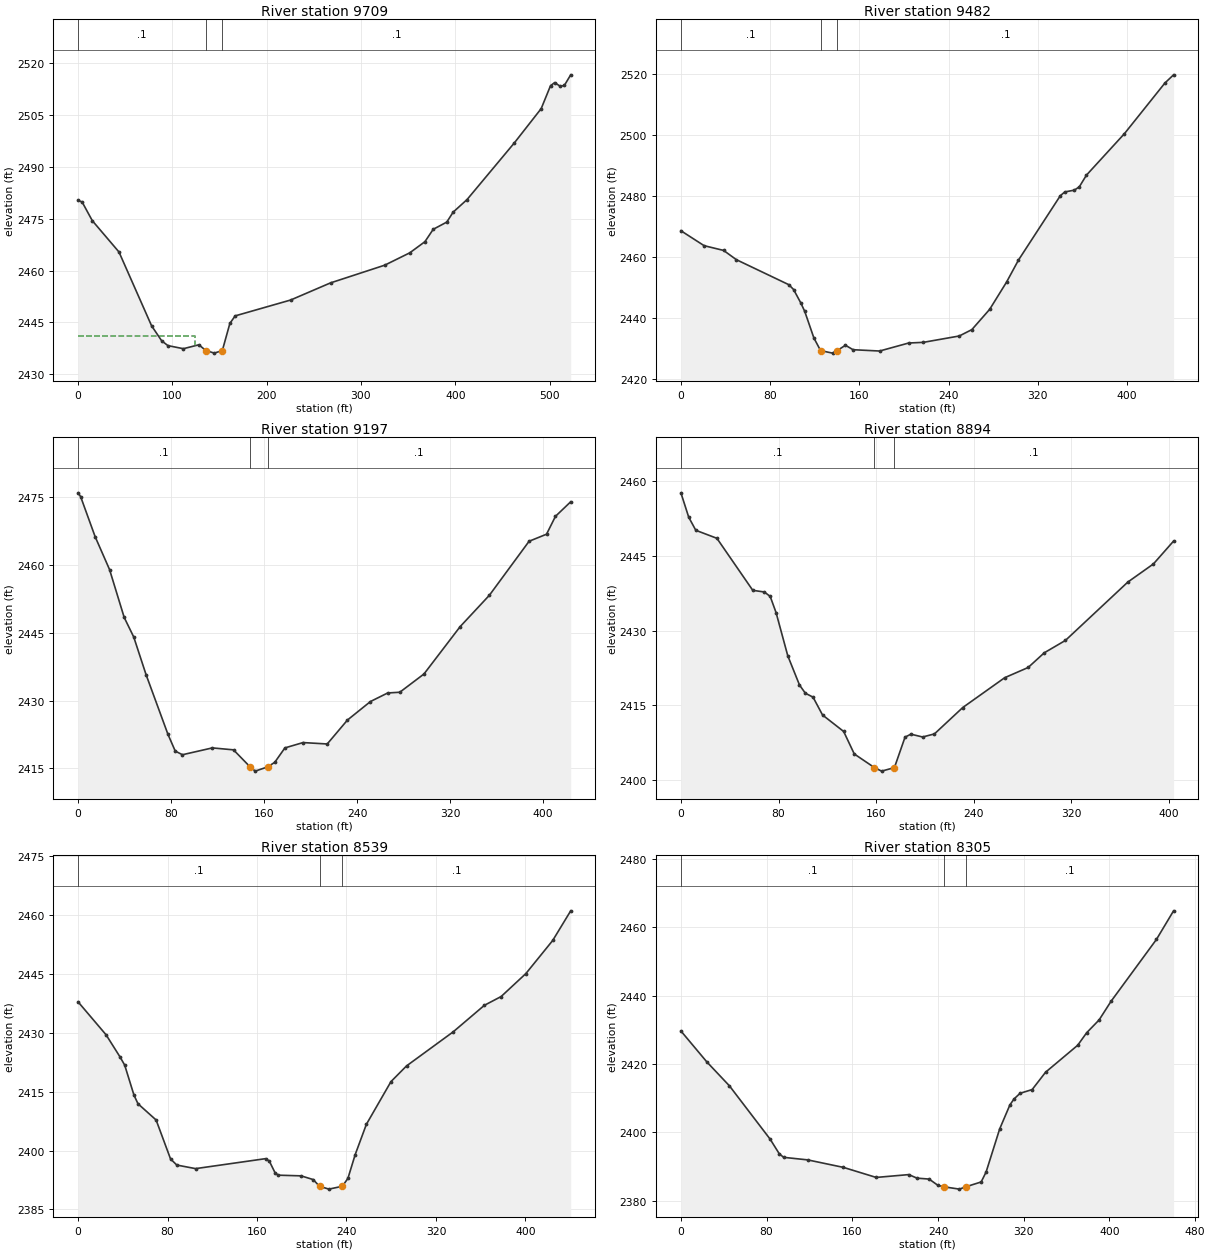
Type RM Length L Ch R = 1 ,9709    ,221.8,227.1,232
XS GIS Cut Line= 4
2203969.34904553624622.6827262082204015.99568042624675.467076216
2204302.01320488624741.7543994822204394.07893164624870.646416944
#Sta/Elev= 30
       0 2480.27     4.3 2479.82    15.1 2474.42    43.4 2465.37      78 2444.03
    88.7  2439.7    95.3 2438.32   111.7 2437.43   128.1 2438.56   135.52436.905
   144.5 2436.15     1532436.902     161 2444.74   166.6 2446.91   225.4 2451.49
   267.7 2456.44   325.2 2461.56   351.7 2465.12   367.8 2468.34   376.6 2471.92
     391 2474.01   397.7 2476.87   412.5 2480.52   462.7 2496.91   491.1 2506.79
     501 2513.41   505.4 2514.31   511.4 2513.21   515.7  2513.5   522.4 2516.55
#Mann= 3 ,-1,0
       0      .1       0   135.5    .045       0     153      .1       0
#XS Ineff= 2 , 0
             124    2441
Permanent Ineff=
       F       F
Bank Sta=135.5,153
XS Rating Curve= 0 ,0
Exp/Cntr(USF)=0,0
Exp/Cntr=0.3,0.1

Type RM Length L Ch R = 1 ,9482    ,285.4,285.5,286
XS GIS Cut Line= 3
2203902.91875772624744.505687826 2203934.9519722624850.789872912
2204157.89138207625094.837324068
#Sta/Elev= 30
       0 2468.75    20.8 2463.85    38.3 2462.29    49.7 2459.26    96.8 2451.04
     101 2449.47   107.5 2445.05     111 2442.29   119.2 2433.58   125.2 2429.44
   135.9 2428.61   140.12429.452   147.5 2431.19   154.3 2429.73   178.1  2429.3
   204.2 2431.93   217.2 2432.14   249.5 2434.23   260.8 2436.32   276.8 2442.99
   291.9 2451.91   302.6 2459.14   340.1 2480.24   344.1 2481.47   352.6 2482.06
   357.1 2483.14   363.5 2486.98   397.5 2500.56   433.9 2517.22   441.6 2519.88
#Mann= 3 ,-1,0
       0      .1       0   125.2    .045       0   140.1      .1       0
Bank Sta=125.2,140.1
XS Rating Curve= 0 ,0
Exp/Cntr=0.3,0.1

Type RM Length L Ch R = 1 ,9197    ,301.6,302.4,303.2
XS GIS Cut Line= 2
2203610.78372838624900.3529581122203881.45696505625226.265630836
#Sta/Elev= 30
       0 2475.97     2.2 2475.14    14.7 2466.26    27.1 2458.98    39.7 2448.38
    47.9 2444.05    58.5 2435.72    77.3 2422.53    83.6  2418.8    89.8    2418
   115.5 2419.51   133.7 2419.08     1482415.301   152.4 2414.37   163.12415.313
   169.2 2416.33   177.9 2419.51   193.5 2420.69   214.3 2420.38   231.7 2425.68
   251.5 2429.78   266.3 2431.67   276.7 2431.83   297.5 2435.87   328.6 2446.35
   353.8 2453.31   387.9 2465.25   402.9 2466.81   410.6 2470.77   423.7 2473.99
#Mann= 3 ,-1,0
       0      .1       0     148    .045       0   163.1      .1       0
Bank Sta=148,163.1
XS Rating Curve= 0 ,0
Exp/Cntr(USF)=0,0
Exp/Cntr=0.3,0.1

Type RM Length L Ch R = 1 ,8894    ,355.1,354.9,353.2
XS GIS Cut Line= 3
2203396.32555673625080.1153455692203448.73280617625159.224424085
2203619.91654844625416.410532275
#Sta/Elev= 30
       0 2457.69     6.4 2452.79    12.2 2450.16    29.5 2448.55    58.9 2438.09
    68.4 2437.76    73.2 2436.86      78 2433.61    87.6 2424.93    97.2 2419.06
     102 2417.41   108.3 2416.62   116.1 2413.03   133.4 2409.72   142.1  2405.2
   158.62402.462   164.5 2401.75     1752402.456   183.7 2408.58   188.5 2409.18
   198.1 2408.61   207.8 2409.23     231 2414.53   265.4 2420.53   284.6 2422.58
   297.8 2425.53   315.2 2428.03   366.3 2439.75   387.3  2443.4   403.8 2447.99
#Mann= 3 ,-1,0
       0      .1       0   158.6    .045       0     175      .1       0
Bank Sta=158.6,175
XS Rating Curve= 0 ,0
Exp/Cntr=0.3,0.1

Type RM Length L Ch R = 1 ,8539    ,234.4,234.4,234.1
XS GIS Cut Line= 4
2203142.11222285625281.0562523322203164.93191865625361.492376493
2203295.71315456625500.7516053192203379.62683322625643.749959027
#Sta/Elev= 30
       0 2437.86    25.1 2429.45    37.4 2423.89    41.7 2421.75      50 2414.11
    53.6  2411.9    69.8 2407.77    82.7 2397.86    88.3  2396.3   105.1 2395.39
   167.7 2397.93     171 2397.31   176.2 2394.31   179.1 2393.72   199.4 2393.55
   210.2 2392.61   215.9  2390.9   224.3 2390.17   236.32390.896   241.3 2392.91
   247.8 2398.96   257.8 2406.67   279.8 2417.55   293.7 2421.54   335.4 2430.21
   363.3 2436.97   378.3 2439.21   400.4 2445.05   424.4 2453.48   440.5 2461.03
#Mann= 3 ,-1,0
       0      .1       0   215.9    .045       0   236.3      .1       0
Bank Sta=215.9,236.3
XS Rating Curve= 0 ,0
Exp/Cntr=0.3,0.1

Type RM Length L Ch R = 1 ,8305    ,209.1,213.4,216.3
XS GIS Cut Line= 3
2202933.25772383625398.2818409062202964.08132915625488.764037164
2203216.63603079625751.261837297
#Sta/Elev= 30
       0 2429.66    24.2 2420.61    45.3 2413.61    83.3 2398.01    91.8 2393.75
    95.9  2392.7   118.4 2391.95   151.7 2389.76   182.3 2386.82   212.7 2387.65
   220.4 2386.61   231.7 2386.34     240 2384.49   245.52384.079     260  2383.4
   265.92384.073   280.3  2385.5   284.9 2388.41   297.6 2401.03   307.1 2408.02
   310.9 2409.75   316.6 2411.43   327.9 2412.52   340.4 2417.59   370.4 2425.48
   378.8 2429.15   390.4 2432.89   401.5 2438.32   443.9 2456.43   459.9  2464.8
#Mann= 3 ,-1,0
       0      .1       0   245.5    .045       0   265.9      .1       0
Bank Sta=245.5,265.9
XS Rating Curve= 0 ,0
Exp/Cntr(USF)=0,0
Exp/Cntr=0.3,0.1

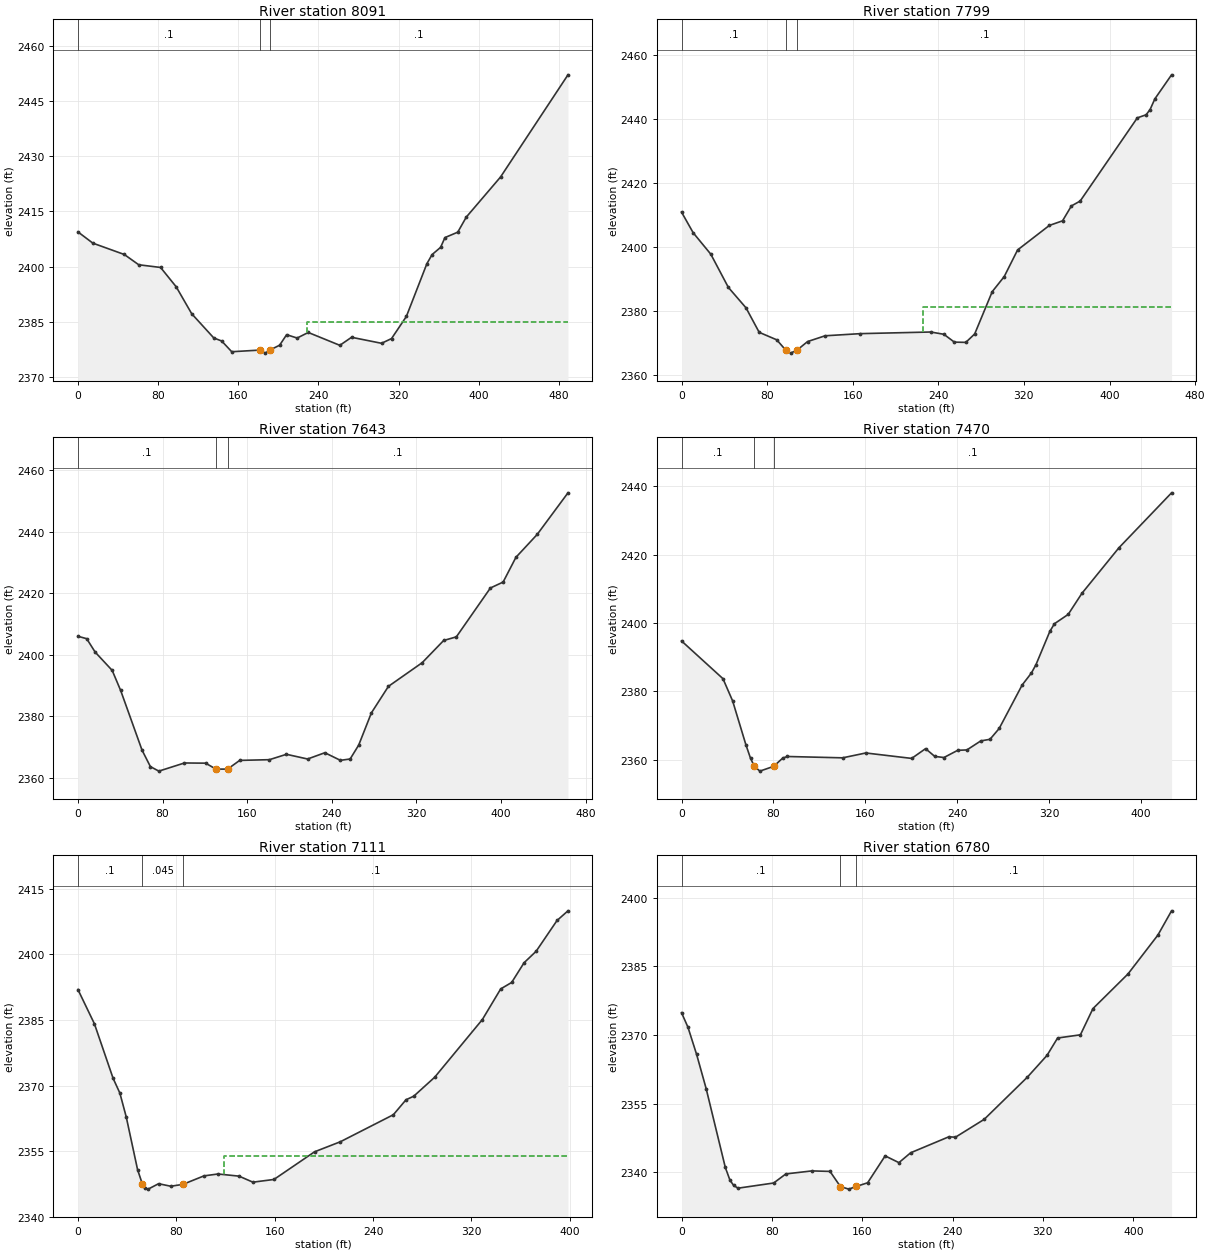
Type RM Length L Ch R = 1 ,8091    ,296.5,292.4,289.3
XS GIS Cut Line= 4
2202752.29333131625537.4852197642202822.88933059625580.240543271
2202964.08132915625770.1537244282203123.17090499625829.812315368
#Sta/Elev= 30
       0 2409.46    14.9  2406.4    46.3 2403.32    60.7 2400.53    82.5  2399.8
    98.1 2394.54   113.6 2387.22   135.6 2380.66   143.5 2379.83   153.5 2376.92
   181.3 2377.36     187 2376.54   191.42377.349   201.3 2378.69   208.3 2381.54
   218.8 2380.64   229.9 2382.15   261.4 2378.66   273.1 2380.84     303 2379.21
     313 2380.49   327.8 2386.49   348.3 2400.83   353.5  2403.3     362 2405.27
   366.3 2407.91   379.1 2409.38   387.6 2413.47   421.8 2424.36   489.1  2452.1
#Mann= 3 ,-1,0
       0      .1       0   181.3    .045       0   191.4      .1       0
#XS Ineff= 2 , 0
                          228.25            2385
Permanent Ineff=
       F       F
Bank Sta=181.3,191.4
XS Rating Curve= 0 ,0
Exp/Cntr(USF)=0,0
Exp/Cntr=0.3,0.1

Type RM Length L Ch R = 1 ,7799    ,156.8,155.9,155.3
XS GIS Cut Line= 2
2202633.52436991 625873.138148342203079.28187674625978.159711964
#Sta/Elev= 30
       0 2410.79    10.9 2404.32    27.4 2397.61    43.8 2387.23    60.3 2380.84
    72.6 2373.19      89 2370.85    97.2 2367.72     102 2366.69   108.22367.689
   117.8  2370.3   134.2 2372.11   167.1 2372.78   232.9 2373.29   245.2 2372.58
     255 2370.13   265.7 2370.05     274 2372.68   290.4 2385.91   301.6 2390.61
   314.1 2398.94   343.8 2406.61   356.1 2408.04   364.4  2412.7   372.6 2414.23
     426 2440.23   434.2 2441.19   437.9 2442.81   442.4 2446.17     458 2453.68
#Mann= 3 ,-1,0
       0      .1       0    97.2    .045       0   108.2      .1       0
#XS Ineff= 2 , 0
                          225.99         2381.15
Permanent Ineff=
       F       F
Bank Sta=97.2,108.2
XS Rating Curve= 0 ,0
Exp/Cntr=0.3,0.1

Type RM Length L Ch R = 1 ,7643    ,174,173.1,171.6
XS GIS Cut Line= 2
2202603.95144859626039.4337742622203065.22512436626082.143973407
#Sta/Elev= 30
       0 2405.96     8.3 2405.17    16.3 2400.81    32.4 2394.86    40.4 2388.34
    60.6 2368.95    68.5 2363.59    76.5 2362.12   100.7 2364.77   120.7 2364.71
   130.5 2362.77   141.5 2362.78   152.9 2365.61     181 2365.84   197.1 2367.59
   217.1 2366.06   233.4  2368.1   248.1 2365.63   257.3 2366.06   265.4 2370.59
   277.4 2381.06   293.5 2389.68   325.4 2397.37   345.7 2404.59   357.7 2405.77
   389.9 2421.66   401.9 2423.58     414 2431.62   434.1 2439.06   463.2 2452.59
#Mann= 3 ,-1,0
       0      .1       0   130.5    .045       0   141.5      .1       0
Bank Sta=130.5,141.5
XS Rating Curve= 0 ,0
Exp/Cntr=0.3,0.1

Type RM Length L Ch R = 1 ,7470    ,352,359.1,365.5
XS GIS Cut Line= 2
2202608.15884697 626202.636729972203033.92198512626230.348918123
#Sta/Elev= 30
       0 2394.73    36.1 2383.68    44.5 2377.19    56.1 2364.32    60.1 2360.39
    63.42358.088    68.2 2356.64    80.2 2358.03    88.2 2360.47    92.2 2360.92
   140.3 2360.53   160.5 2361.95   200.4 2360.36   212.5 2363.21   220.5 2360.95
   228.5 2360.62   240.5 2362.73   248.5 2362.84   260.6 2365.48   268.6 2365.95
   276.6 2369.11   296.6 2381.83   304.7 2385.36   308.7 2387.83   320.7  2397.5
   324.7 2399.75   336.7 2402.49   348.6 2408.63   380.8 2421.95   426.7 2438.05
#Mann= 3 ,-1,0
       0      .1       0    63.4    .045       0    80.2      .1       0
Bank Sta=63.4,80.2
XS Rating Curve= 0 ,0
Exp/Cntr(USF)=0,0
Exp/Cntr=0.3,0.1

Type RM Length L Ch R = 1 ,7111    ,328.9,331,329.8
XS GIS Cut Line= 2
2202489.79553118626451.2559709872202798.03158437 626703.81067263
#Sta/Elev= 30
       0 2391.99    13.4 2384.16    28.6 2371.69    34.1 2368.32    39.3 2362.85
    48.5 2350.81    52.52347.436    54.2 2346.57    57.1 2346.35    65.6 2347.59
    75.5 2347.01    85.3 2347.43   102.5 2349.38   113.9 2349.81     131 2349.32
   142.3 2347.94   159.4 2348.56   192.4 2354.88   213.4 2357.18   256.5 2363.36
   266.8 2366.78   273.1  2367.6   290.1 2371.93   328.9 2385.13   343.8 2392.13
   352.7  2393.6   362.8 2398.11   372.6 2400.73   389.6 2407.77   398.5 2409.98
#Mann= 3 ,-1,0
       0      .1       0    52.5    .045       0    85.3      .1       0
#XS Ineff= 1 ,-1
  118.99398.4888 2353.98
Permanent Ineff=
       F
Bank Sta=52.5,85.3
XS Rating Curve= 0 ,0
Exp/Cntr(USF)=0,0
Exp/Cntr=0.3,0.1

Type RM Length L Ch R = 1 ,6780    ,301,302,302.5
XS GIS Cut Line= 2
2202237.24082954626629.2374339562202550.44843197626929.519008351
#Sta/Elev= 30
       0 2374.89     5.7 2371.71    13.4 2365.73    21.8 2358.28    38.8 2340.99
    42.9 2338.21    46.2 2337.05    50.1 2336.46    81.6 2337.59    92.4 2339.58
   115.5 2340.24   131.5 2340.13   140.7 2336.81   148.1 2336.25   154.8 2336.84
   164.8 2337.64   180.3 2343.53   192.5 2342.05   202.9 2344.21   236.8 2347.72
   242.5 2347.61     268 2351.53   306.2 2360.76   323.6 2365.53     333 2369.34
   353.2 2370.04   364.3 2375.78   395.3 2383.36   421.8 2391.88   433.9 2397.19
#Mann= 3 ,-1,0
       0      .1       0   140.7    .045       0   154.8      .1       0
Bank Sta=140.7,154.8
XS Rating Curve= 0 ,0
Exp/Cntr(USF)=0,0
Exp/Cntr=0.3,0.1

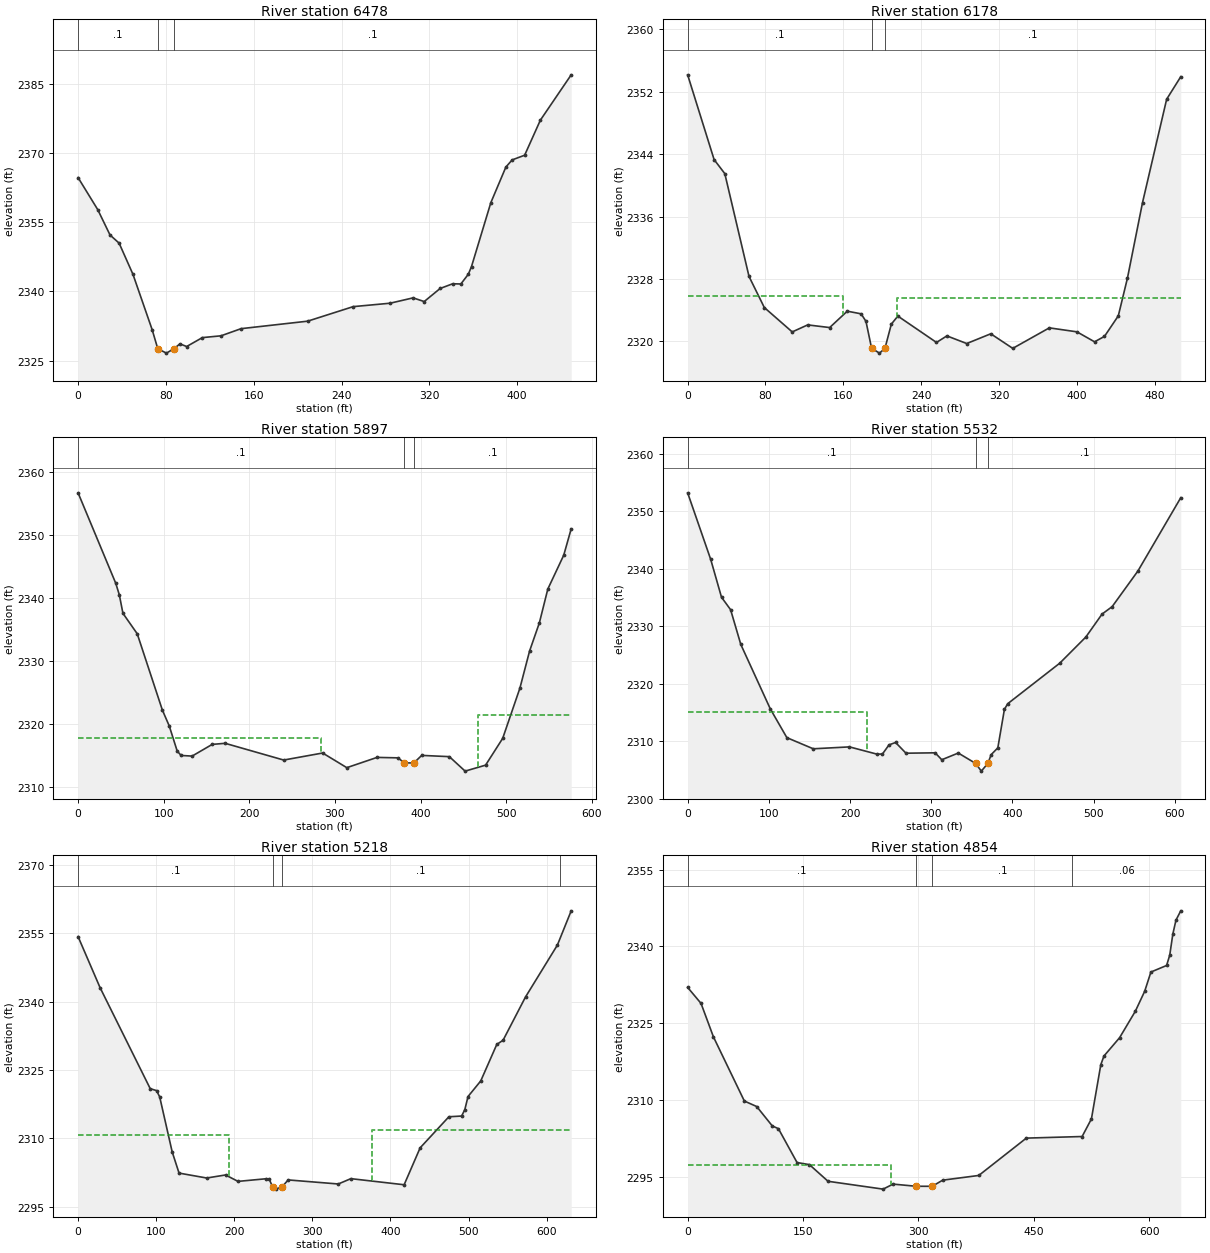
Type RM Length L Ch R = 1 ,6478    ,299.5,300.2,300.7
XS GIS Cut Line= 3
 2202050.9658778626749.3743220632202069.20246506626809.207516623
2202305.66762547 627115.16182817
#Sta/Elev= 30
       0 2364.66    17.9 2357.73    29.1 2352.23    37.4 2350.46      50 2343.71
    67.5 2331.71    72.6 2327.59    80.5 2326.64    87.4 2327.61    92.8 2328.65
    98.9 2328.07   113.2    2330   130.2 2330.39   148.5 2331.94   209.1 2333.56
   250.6 2336.71   284.2 2337.45   305.2 2338.61   315.3 2337.81   329.8 2340.64
   341.2 2341.66   348.7 2341.62   355.5 2343.73   358.4  2345.4     376 2359.23
   389.7 2366.94   395.4 2368.49   406.8 2369.51   421.1 2377.09   449.2 2386.92
#Mann= 3 ,-1,0
       0      .1       0    72.6    .045       0    87.4      .1       0
Bank Sta=72.6,87.4
XS Rating Curve= 0 ,0
Exp/Cntr=0.3,0.1

Type RM Length L Ch R = 1 ,6178    ,278.7,280.9,277.7
XS GIS Cut Line= 2
2201754.64605796626858.100724164 2202023.8819276627287.575219068
#Sta/Elev= 30
       0 2354.17    27.2  2343.3    38.2  2341.5    63.1 2328.31    78.8 2324.33
   107.5  2321.2   123.4  2322.1     146 2321.76   164.1 2323.86   178.3 2323.52
   183.3 2322.56   189.1  2319.1   197.2 2318.48   202.82319.083   209.4  2322.2
   216.1 2323.23   255.8 2319.85   266.5 2320.69   286.9 2319.71   311.6 2320.96
   334.2 2319.09   371.8 2321.72   400.2 2321.21   418.3 2319.93   428.5 2320.63
   442.7 2323.26   452.1  2328.1   467.6 2337.79   492.4 2351.04   506.9 2353.93
#Mann= 3 ,-1,0
       0      .1       0   189.1    .045       0   202.8      .1       0
#XS Ineff= 2 , 0
          159.56 2325.77  214.87         2325.59
Permanent Ineff=
       F       F
Bank Sta=189.1,202.8
XS Rating Curve= 0 ,0
Exp/Cntr=0.3,0.1

Type RM Length L Ch R = 1 ,5897    ,359.4,365.2,365.2
XS GIS Cut Line= 4
2201580.30503838626915.2715663062201613.66973577627020.352494082
2201790.29948372627329.6091093292201856.72325442627416.848890655
#Sta/Elev= 30
       0 2356.71      44 2342.34    48.2 2340.49    52.4 2337.56    69.1 2334.31
    98.5 2322.17   106.5 2319.66   115.8 2315.66   120.4 2314.97   133.2 2314.87
   156.7 2316.73   171.8  2316.9   240.2 2314.24   285.7 2315.36   313.9 2313.03
   349.2 2314.66   373.8 2314.59   380.92313.789   392.2 2313.78   401.4 2314.98
   433.7 2314.78   452.1 2312.48     476 2313.43     496 2317.69   516.1 2325.67
   527.4 2331.57   538.8 2336.03   548.7 2341.42   567.3  2346.8     576 2350.99
#Mann= 3 ,-1,0
       0      .1       0   380.9    .045       0   392.2      .1       0
#XS Ineff= 2 , 0
          284.19 2317.77  466.67         2321.35
Permanent Ineff=
       F       F
Bank Sta=380.9,392.2
XS Rating Curve= 0 ,0
Exp/Cntr=0.3,0.1

Type RM Length L Ch R = 1 ,5532    ,310.4,313.7,313
XS GIS Cut Line= 4
 2201430.9578633626953.3105010942201452.93960004627063.131191422
2201502.17328656627349.1181941232201513.00737346627553.988049703
#Sta/Elev= 30
       0 2353.23    28.4 2341.64    41.7 2335.05    52.9 2332.88    65.5 2326.82
   101.8 2315.61   122.2  2310.6   154.7 2308.66   199.3 2308.99   233.1 2307.73
   239.9 2307.75     248 2309.34   256.1 2309.76   268.9 2307.89   304.8 2307.96
     313 2306.75   333.3 2307.92   354.7 2306.11   361.7 2304.77   369.8 2306.13
   373.8 2307.64     382 2308.82   390.1 2315.51   394.1  2316.5   458.3 2323.57
   490.4 2328.12   510.4 2332.12   522.8 2333.41   554.5 2339.61   607.3 2352.38
#Mann= 3 ,-1,0
       0      .1       0   354.7    .045       0   369.8      .1       0
#XS Ineff= 2 , 0
          220.58 2315.04
Permanent Ineff=
       F       F
Bank Sta=354.7,369.8
XS Rating Curve= 0 ,0
Exp/Cntr=0.3,0.1

Type RM Length L Ch R = 1 ,5218    ,358.1,363.8,361.1
XS GIS Cut Line= 3
 2201192.9761826626965.0408993452201226.66956657 627380.21555658
2201270.95795542627590.499390351
#Sta/Elev= 30
       0 2354.31    28.2 2343.09    92.4 2320.92   100.5 2320.49   104.5 2319.12
   120.5 2307.04   129.3 2302.38   164.7  2301.3   188.8 2301.97   204.8 2300.56
   240.9 2301.14   244.9 2300.98     249 2299.38     253 2298.86   261.42299.401
     269 2300.88   333.2 2299.99   349.3 2301.16   417.5 2299.82     438 2307.93
   474.8 2314.75   491.1 2314.91   495.2 2316.32   499.3 2319.19   515.6 2322.62
   536.1 2330.62   544.2 2331.56   572.9 2341.05   613.7 2352.44   631.4 2359.97
#Mann= 4 ,-1,0
       0      .1       0     249    .045       0   261.4      .1       0
  616.54     .06       0
#XS Ineff= 2 , 0
          193.81 2310.69  376.14         2311.79
Permanent Ineff=
       F       F
Bank Sta=249,261.4
XS Rating Curve= 0 ,0
Exp/Cntr=0.3,0.1

Type RM Length L Ch R = 1 ,4854    ,193.2,196.7,196
XS GIS Cut Line= 3
2200901.77903222626983.939501158  2200962.431933627503.963552179
2200984.30674968627619.303494662
#Sta/Elev= 30
       0 2332.01    17.4 2328.89    33.5 2322.36    73.7 2309.83    89.8 2308.75
     110 2304.97     118 2304.43   142.2 2297.82   158.3 2297.41   182.5 2294.16
     254 2292.63     267 2293.61   296.9 2293.19   317.8 2293.18   331.5 2294.38
   378.4  2295.3   440.2 2302.59   512.7  2302.9   524.8 2306.34     537 2316.93
   541.1 2318.62   561.4 2322.19   581.8 2327.34     594 2331.25   602.1 2335.01
   622.5 2336.29   626.6 2338.32   630.6 2342.43   634.7 2345.15   640.9 2346.96
#Mann= 4 ,-1,0
       0      .1       0   296.9    .045       0   317.8      .1       0
     500     .06       0
#XS Ineff= 2 , 0
          264.84 2297.37
Permanent Ineff=
       F       F
Bank Sta=296.9,317.8
XS Rating Curve= 0 ,0
Exp/Cntr(USF)=0,0
Exp/Cntr=0.3,0.1

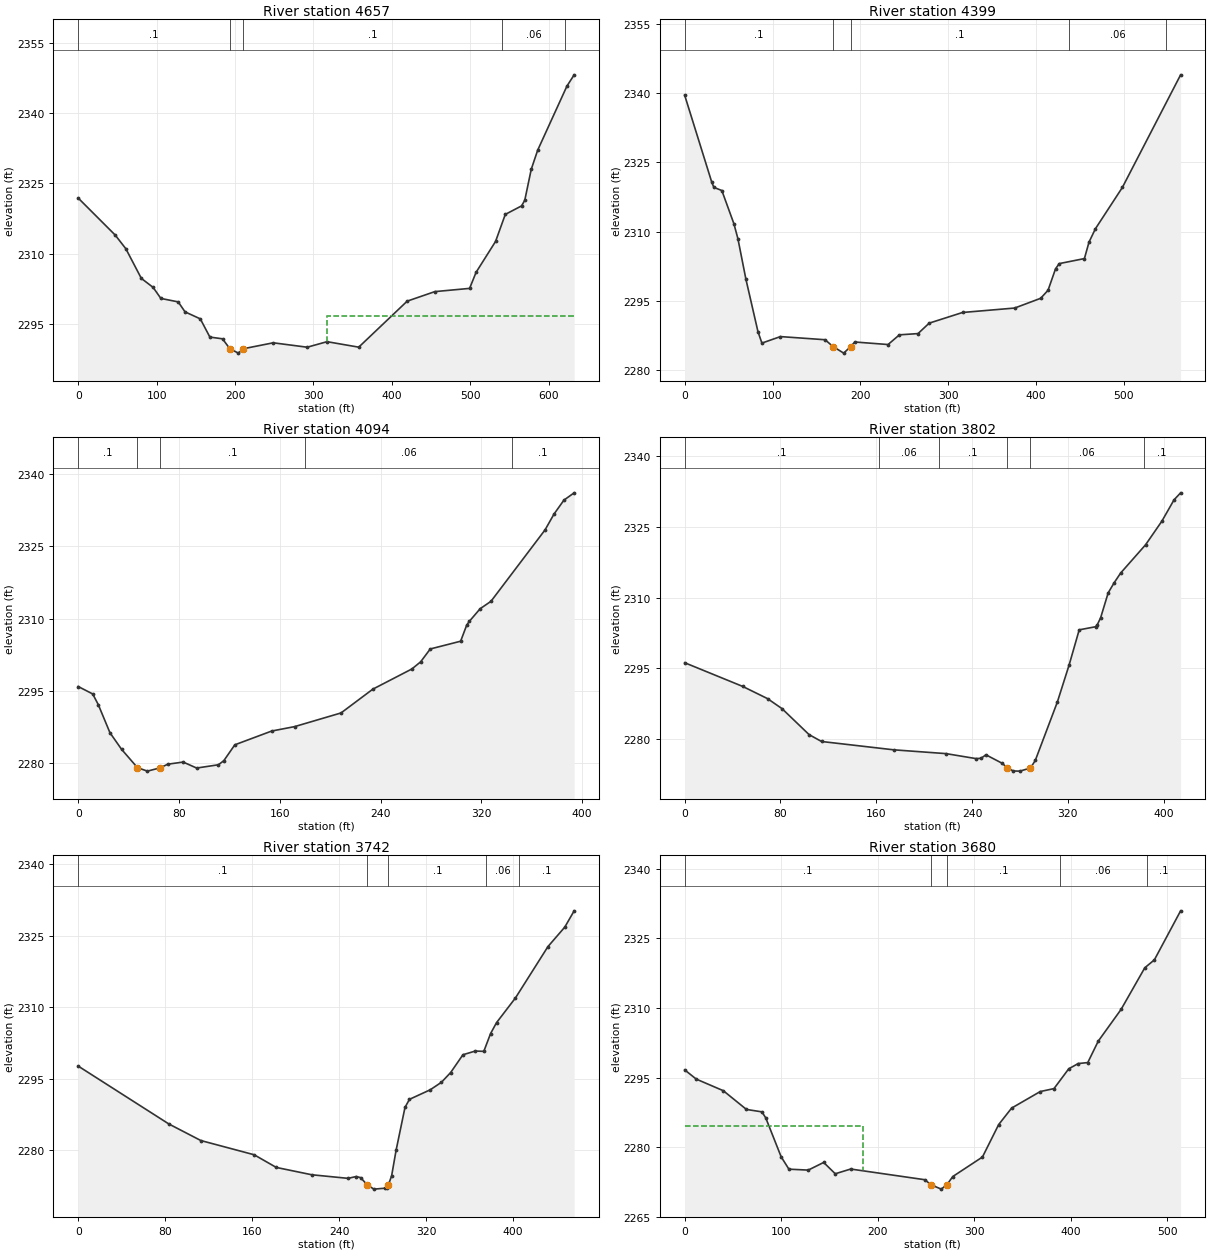
Type RM Length L Ch R = 1 ,4657    ,260.7,258.9,257.9
XS GIS Cut Line= 4
2200684.02517529 627060.501359532200752.63255487627152.972175486
2200806.32528671627534.7871574982200840.13182158627662.058818169
#Sta/Elev= 30
       0 2321.88    47.2 2313.99    60.7 2311.09    80.5 2304.76    95.5 2302.84
   105.4 2300.49   127.5 2299.75   136.2 2297.63   155.7 2296.13   167.9 2292.25
     184 2291.88   193.42289.758   204.2 2288.83   210.32289.757   248.7 2291.03
     292 2290.09   317.3 2291.27   357.7  2290.1   419.5 2299.91   454.7 2301.94
   499.1 2302.63   507.3 2306.04   532.2 2312.64   544.6  2318.4   565.3 2320.21
   569.4 2321.39   577.7 2328.02   585.9 2332.09   623.2 2345.75   632.4 2348.15
#Mann= 5 ,-1,0
       0      .1       0   193.4    .045       0   210.3      .1       0
  540.71     .06       0  620.71      .1       0
#XS Ineff= 1 ,-1
   316.9632.3995 2296.78
Permanent Ineff=
       F
Bank Sta=193.4,210.3
XS Rating Curve= 0 ,0
Exp/Cntr(USF)=0,0
Exp/Cntr=0.3,0.1

Type RM Length L Ch R = 1 ,4399    ,312.7,304.8,297
XS GIS Cut Line= 3
 2200467.5079778627168.0257687492200509.45053979  627244.7949694
2200664.76691114627695.823847039
#Sta/Elev= 30
       0 2339.53    30.8 2320.72    33.2 2319.59    42.3  2318.9      56 2311.73
    60.6 2308.47    69.7  2299.7    83.4 2288.36    87.9 2285.87     109 2287.28
   159.8  2286.6   168.82285.134     181  2283.7     1892285.134   193.6 2286.11
   231.5 2285.56   244.4 2287.66   265.6 2287.93   278.3 2290.19   316.3  2292.5
   375.6 2293.46   405.2 2295.57   413.6 2297.31   422.1 2301.94   426.3 2303.08
     455 2304.17   460.2 2307.72   467.5 2310.62   498.2 2319.57   564.5 2343.95
#Mann= 5 ,-1,0
       0      .1       0   168.8    .045       0     189      .1       0
  437.48     .06       0  547.48      .1       0
Bank Sta=168.8,189
XS Rating Curve= 0 ,0
Exp/Cntr=0.3,0.1

Type RM Length L Ch R = 1 ,4094    ,286.5,292.1,299.3
XS GIS Cut Line= 3
2200281.52723081627506.8000915622200534.25167109627612.749274676
2200601.07923604627711.852137325
#Sta/Elev= 30
       0 2295.93    11.5 2294.39    15.9 2292.19    25.2 2286.34    34.4 2282.91
      472279.103    54.9 2278.38      65 2279.06    71.1 2279.82    83.3 2280.26
      94 2279.02   111.3  2279.7   115.6 2280.56   124.3 2283.84   153.6  2286.7
   171.7 2287.61   208.6 2290.45   233.8 2295.38   264.8 2299.57   271.8 2301.06
   279.4 2303.72   303.5 2305.33   308.3 2308.65   310.3 2309.42     319 2312.07
   327.6 2313.61   370.5 2328.42   377.6  2331.7   385.5  2334.6   393.6 2336.11
#Mann= 5 ,-1,0
       0      .1       0      47    .045       0      65      .1       0
     180     .06       0  344.03      .1       0
Bank Sta=47,65
XS Rating Curve= 0 ,0
Exp/Cntr(USF)=0,0
Exp/Cntr=0.3,0.1

Type RM Length L Ch R = 1 ,3802    ,53.5,59.2,67
XS GIS Cut Line= 5
2200246.36919582627512.6092769572200261.27257522627623.763648353
2200237.67555783 627761.619907852200282.38569604 627841.10459801
 2200327.7168084627895.750322495
#Sta/Elev= 30
       0 2296.14    48.4 2291.11    69.2 2288.51    81.3 2286.38   103.9 2280.86
   114.3  2279.4   174.5 2277.63   218.3 2276.82   243.4 2275.76   247.5 2275.83
   251.6 2276.57   265.3 2274.75   269.52273.764   274.5 2273.13     280  2273.1
   288.8 2273.77   292.8 2275.36   311.2 2287.75   321.1 2295.68   329.5 2303.13
   343.2 2303.79   344.5 2304.16   347.4  2305.7   353.7 2310.99   358.7 2313.14
   364.1  2315.2   384.9  2321.2   398.5 2326.21   408.7 2330.76   414.2 2332.25
#Mann= 6 ,-1,0
       0      .1       0  162.15     .06       0  212.15      .1       0
   269.5    .045       0   288.8     .06       0  383.21      .1       0
Bank Sta=269.5,288.8
XS Rating Curve= 0 ,0
Exp/Cntr(USF)=0,0
Exp/Cntr=0.3,0.1

Type RM Length L Ch R = 1 ,3742    ,58.8,62.1,65.2
XS GIS Cut Line= 4
2200218.34335485627521.7282717652200229.73272172627604.378123618
 2200183.4330259 627831.85266859 2200290.4912903627923.033478073
#Sta/Elev= 30
       0 2297.68    83.4 2285.54   112.8 2282.07   161.8 2279.09   182.2 2276.43
   214.9 2274.89   248.2 2274.14   255.7 2274.52   259.8 2274.29   265.92272.762
     272 2271.88   282.1 2272.07   284.3 2272.22   285.32272.753   288.3 2274.67
   292.4 2280.02   300.6 2289.02   304.7 2290.71   323.8 2292.71   334.1 2294.28
   342.6 2296.33   353.9 2300.06   365.3 2300.84   373.1 2300.77   379.3 2304.49
   384.8 2306.79   402.2 2311.97   432.1 2322.74   447.6 2326.83   456.2 2330.24
#Mann= 5 ,-1,0
       0      .1       0   265.9    .045       0   285.3      .1       0
  375.57     .06       0  405.57      .1       0
Bank Sta=265.9,285.3
XS Rating Curve= 0 ,0
Exp/Cntr=0.3,0.1

Type RM Length L Ch R = 1 ,3680    ,28.5,30.8,30.8
XS GIS Cut Line= 6
 2200168.4260935627533.1724615982200165.77411998627741.867519444
2200132.86589435627778.617430211 2200118.7747738627800.928371075
2200107.64824773  627822.27250472200274.29429007627942.195151675
#Sta/Elev= 30
       0 2296.65      12 2294.66      40 2292.16      64 2288.12      80  2287.6
      84  2286.3     100 2277.89     108 2275.25     128 2275.05     144  2276.7
     156 2274.26     172 2275.28     249 2272.97   254.7 2271.94   265.8 2270.95
   271.8 2271.94   277.8 2273.67   308.5 2277.87   325.3 2284.86   338.7 2288.41
   368.4 2291.98   382.6 2292.61   397.9 2296.88   407.7 2298.01   417.6 2298.22
   428.5 2302.85   452.1 2309.67   476.7 2318.65   486.6 2320.35   513.8 2330.92
#Mann= 5 ,-1,0
       0      .1       0   254.7    .045       0   271.8      .1       0
   388.5     .06       0   478.5      .1       0
#XS Ineff= 2 , 0
           184.7 2284.59
Permanent Ineff=
       F       F
Bank Sta=254.7,271.8
XS Rating Curve= 0 ,0
Exp/Cntr(USF)=0,0
Exp/Cntr=0.3,0.1