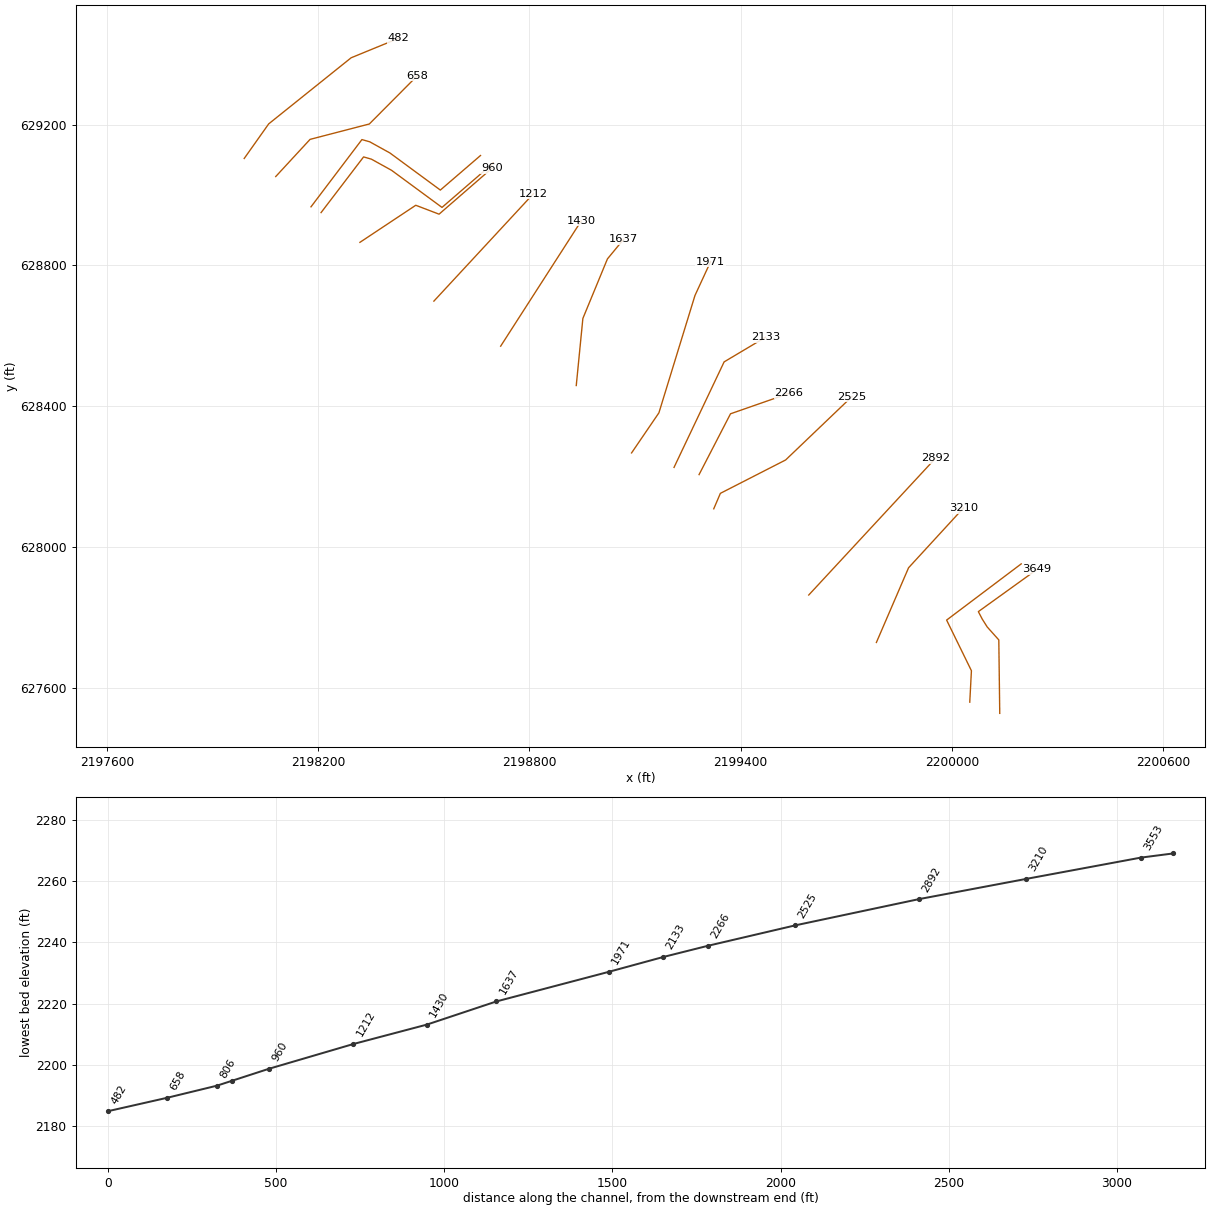
HEC-RAS study TROUTRN.prj: TROUTRN

--- TROUTRN.g01 (geometry) --- (continued)

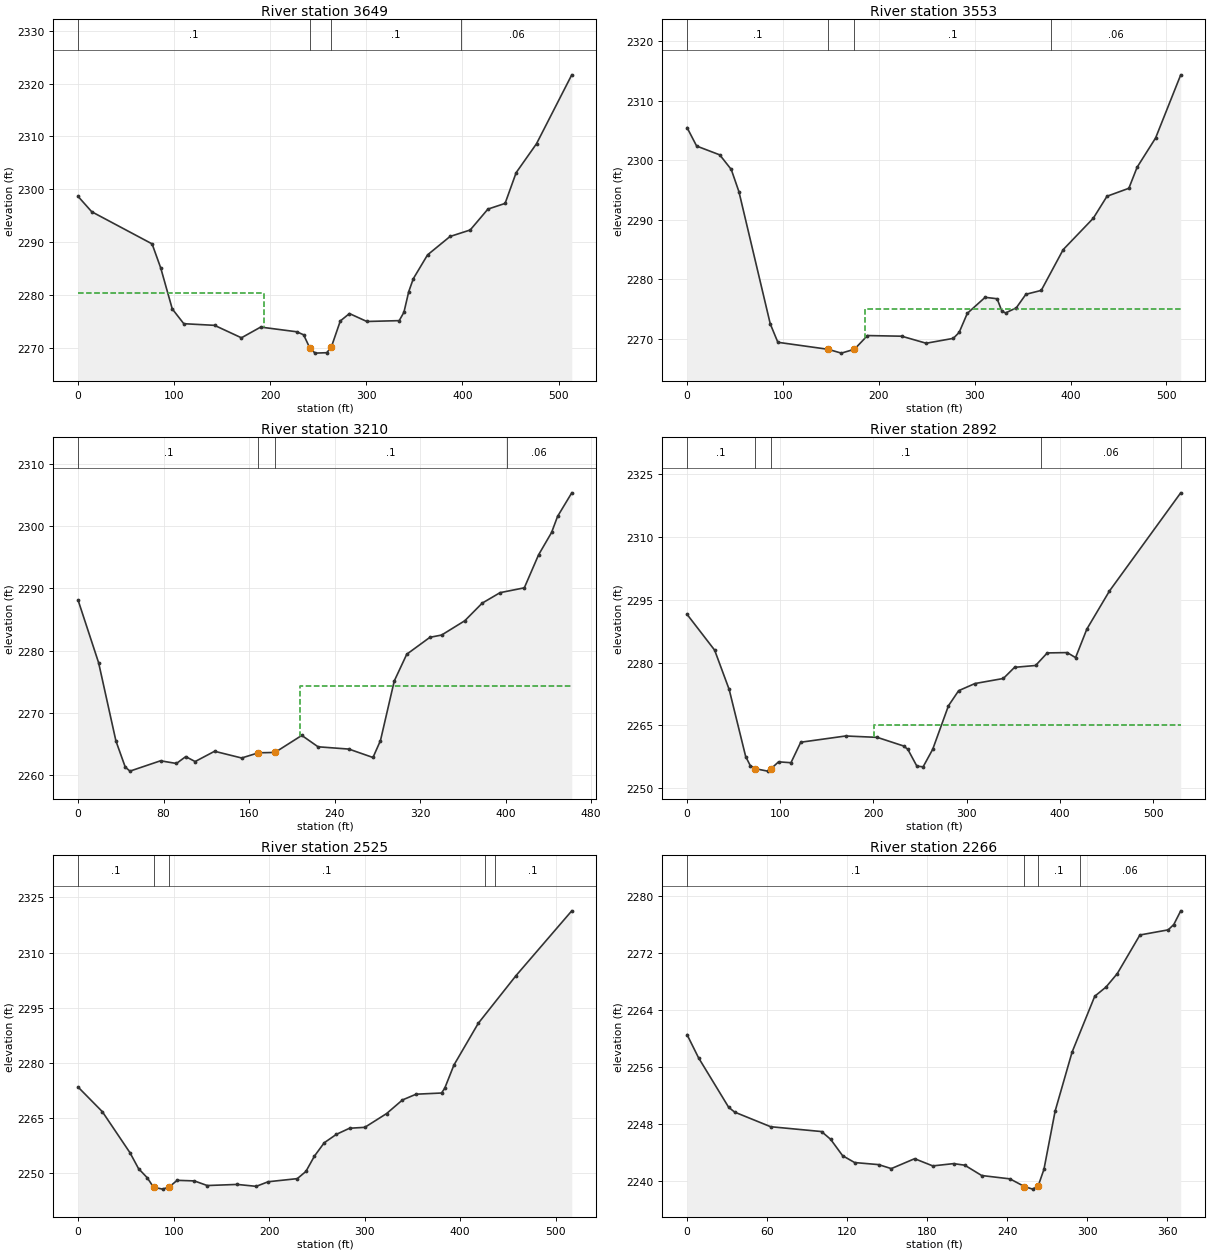
Type RM Length L Ch R = 1 ,3649    ,101.3,96.9,95.2
XS GIS Cut Line= 6
2200136.13334672 627527.17849809 2200133.4813732627735.873555936
2200100.57314757627772.6234667032200086.48202702627794.934407567
2200075.35550094627816.2785411922200242.00154328627936.201188167
#Sta/Elev= 30
       0 2298.64    14.2 2295.74      77 2289.66      86  2285.1      98 2277.35
     110 2274.55     142 2274.24     170 2271.88     190 2273.91   227.6 2273.02
   234.7 2272.45     2412270.021   246.6 2268.98   258.7 2269.06   263.4 2270.05
   272.9 2275.07   282.4 2276.47   300.5 2274.97   334.2 2275.13   339.1 2276.71
   344.1 2280.61   348.9 2283.08   363.7 2287.58   387.1 2291.06   408.1 2292.29
   426.5 2296.24   444.4 2297.32   455.9 2303.14   477.1 2308.62   513.8 2321.66
#Mann= 4 ,-1,0
       0      .1       0     241    .045       0   263.4      .1       0
   398.5     .06       0
#XS Ineff= 2 , 0
          193.44 2280.32
Permanent Ineff=
       F       F
Bank Sta=241,263.4
XS Rating Curve= 0 ,0
Exp/Cntr(USF)=0,0
Exp/Cntr=0.3,0.1

Type RM Length L Ch R = 1 ,3553    ,356.9,342.4,330.5
XS GIS Cut Line= 4
2200050.96098069627559.1480073192200055.65802087627648.391770774
2199985.20241814627792.2386263432200197.15635635627951.937992525
#Sta/Elev= 30
       0 2305.48      10 2302.38    34.1  2300.9    46.1 2298.45    54.1 2294.72
    86.8 2272.51    94.7 2269.43   147.2 2268.25   160.9 2267.61   174.52268.255
   188.2 2270.56   223.9 2270.45   249.4 2269.27   277.7 2270.09   283.8 2271.09
   292.3 2274.29   310.9 2276.98   323.4 2276.74   328.4 2274.64   332.3 2274.36
   343.4 2275.22   353.4 2277.49   369.4 2278.14   392.3 2284.99   423.7 2290.26
     438 2293.95   460.8 2295.29   469.4 2298.82   488.7 2303.74   514.9 2314.34
#Mann= 4 ,-1,0
       0      .1       0   147.2    .045       0   174.5      .1       0
  379.54     .06       0
#XS Ineff= 2 , 0
                          185.24            2275
Permanent Ineff=
       F       F
Bank Sta=147.2,174.5
XS Rating Curve= 0 ,0
Exp/Cntr(USF)=0,0
Exp/Cntr=0.3,0.1

Type RM Length L Ch R = 1 ,3210    ,314.3,317.8,307.6
XS GIS Cut Line= 3
2199785.66484211627728.6534721862199877.08627193627940.869627514
2200033.21509129628110.897633707
#Sta/Elev= 30
       0  2288.1    19.2 2278.05    35.4 2265.48    44.1  2261.3    48.5 2260.64
    77.1  2262.3      92 2261.87   100.7 2262.97   109.5 2262.18   127.7 2263.83
     153 2262.75   168.72263.584   184.22263.641   209.3 2266.38   224.5 2264.55
   253.4 2264.18   275.9 2262.83   282.9 2265.55   295.8 2275.12   307.5 2279.42
   329.2 2282.14   340.1  2282.5   361.8  2284.8   378.1 2287.63   394.8 2289.31
   417.5 2290.09   430.8 2295.38     443 2298.98   448.6 2301.56   461.9 2305.35
#Mann= 4 ,-1,0
       0      .1       0   168.7    .045       0   184.2      .1       0
  401.07     .06       0
#XS Ineff= 2 , 0
                          207.65         2274.25
Permanent Ineff=
       F       F
Bank Sta=168.7,184.2
XS Rating Curve= 0 ,0
Exp/Cntr=0.3,0.1

Type RM Length L Ch R = 1 ,2892    ,370.5,367.7,364.8
XS GIS Cut Line= 2
2199593.43846422627863.4370308492199953.53504859628251.938057105
#Sta/Elev= 30
       0  2291.5    29.6 2282.95    45.2 2273.56    62.9 2257.56    67.8  2255.4
    73.3 2254.65    86.4 2254.07    90.22254.665    98.2 2256.29   111.5 2256.08
     122 2260.97   170.2 2262.46   204.1 2262.13   232.4 2260.07   236.9 2259.27
   246.6 2255.26   253.3  2255.1   263.6 2259.29   280.5 2269.68   291.4 2273.27
   308.9 2274.98   339.4 2276.19   351.4 2278.85     374 2279.29   386.5 2282.29
   407.9 2282.37   416.9 2281.17     429 2287.99   453.2 2297.06   529.7 2320.51
#Mann= 5 ,-1,0
       0      .1       0    73.3    .045       0    90.2      .1       0
     380     .06       0  529.72      .1       0
#XS Ineff= 2 , 0
                        200.4873            2265
Permanent Ineff=
       F       F
Bank Sta=73.3,90.2
XS Rating Curve= 0 ,0
Exp/Cntr=0.3,0.1

Type RM Length L Ch R = 1 ,2525    ,260.3,258.6,255.2
XS GIS Cut Line= 4
2199323.54679001628108.3948917852199342.43105963628152.341238325
2199527.82497965628247.1814168982199716.36589811628427.392421266
#Sta/Elev= 30
       0 2273.33    25.4 2266.62    54.3 2255.45    63.3  2251.1    72.3 2248.65
      792246.045    88.4 2245.52    95.3 2246.09   103.7 2247.92   121.7 2247.76
   135.2  2246.5   166.6  2246.8   186.5 2246.28     199 2247.53   229.5 2248.38
   238.5 2250.33   247.5 2254.54   257.7 2258.15   270.5 2260.46   284.2 2262.11
   300.2 2262.36     323 2266.11   339.6 2269.82   353.9 2271.39   380.5 2271.71
   383.8 2272.97   393.5 2279.33     419 2290.71   458.6 2303.73   516.9 2321.36
#Mann= 5 ,-1,0
       0      .1       0      79    .045       0    95.3      .1       0
  426.08     .06       0  436.08      .1       0
Bank Sta=79,95.3
XS Rating Curve= 0 ,0
Exp/Cntr=0.3,0.1

Type RM Length L Ch R = 1 ,2266    ,121.9,133.2,136.5
XS GIS Cut Line= 3
2199281.81131638628205.5048305682199371.17326552628378.336732202
2199537.13117107628436.274699227
#Sta/Elev= 30
       0 2260.57     8.6 2257.33    31.2 2250.38    35.7  2249.7    62.7 2247.65
   100.9 2246.97   107.7 2245.88   116.7 2243.58   125.7 2242.62   143.7 2242.33
   153.2 2241.77   170.7 2243.16   184.3 2242.15   199.9 2242.47   208.3 2242.25
     221  2240.8   242.2 2240.33   253.12239.254   259.2 2238.89   263.3  2239.3
   267.7 2241.67   276.1 2249.85   288.8 2258.12   305.8 2265.96   314.3 2267.26
   322.7 2269.14   339.7 2274.56   360.9 2275.28   365.1 2276.03   370.3 2277.95
#Mann= 4 ,-1,0
       0      .1       0   253.1    .045       0   263.3      .1       0
  294.57     .06       0
Bank Sta=253.1,263.3
XS Rating Curve= 0 ,0
Exp/Cntr(USF)=0,0
Exp/Cntr=0.3,0.1

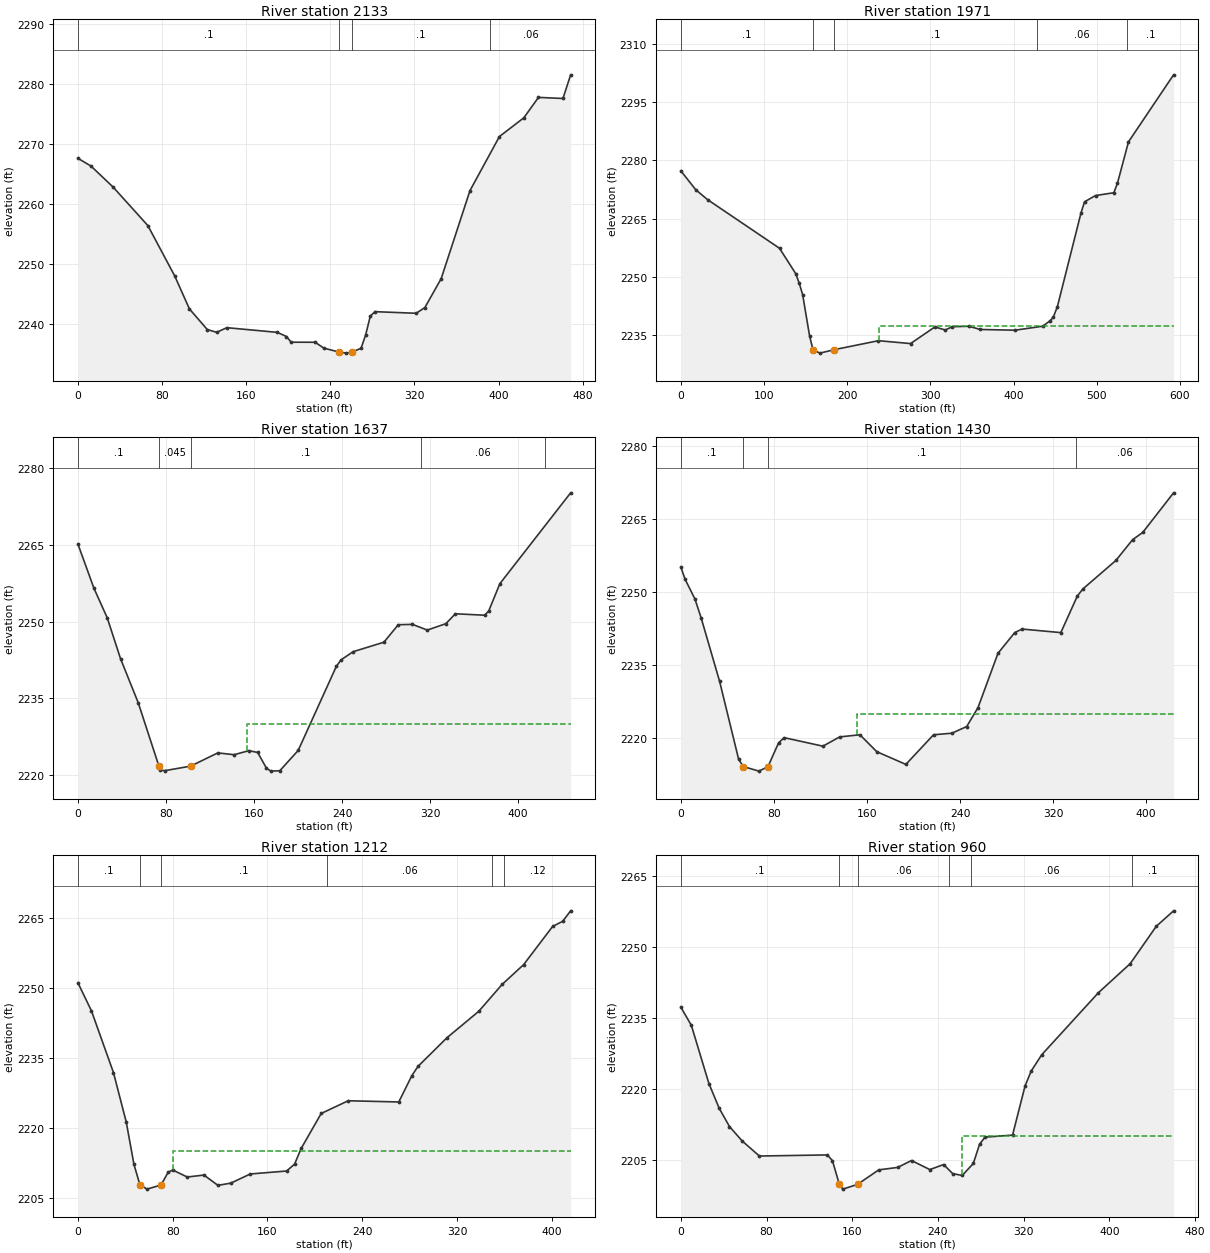
Type RM Length L Ch R = 1 ,2133    ,148.6,162.3,159.3
XS GIS Cut Line= 3
 2199210.7249971628226.0208768192199353.03819033 628525.82219842
 2199470.4727915628595.701948059
#Sta/Elev= 30
       0 2267.69    12.4  2266.4    33.5 2262.89    66.5 2256.48    92.1 2248.07
     106  2242.6     123 2239.16   131.9  2238.7   141.6 2239.47   189.6 2238.69
   198.3    2238   202.7 2237.05   225.6 2237.04   233.7 2236.07     248 2235.42
   255.2 2235.23   260.3  2235.4   269.2 2236.03   273.6 2238.27     278  2241.4
   282.4 2242.14   321.7 2241.87   329.9 2242.83   345.4 2247.64   372.8 2262.32
   400.8 2271.32     424 2274.44   437.9 2277.84   461.2 2277.66   468.5  2281.6
#Mann= 4 ,-1,0
       0      .1       0     248    .045       0   260.3      .1       0
  391.86     .06       0
Bank Sta=248,260.3
XS Rating Curve= 0 ,0
Exp/Cntr(USF)=0,0
Exp/Cntr=0.3,0.1

Type RM Length L Ch R = 1 ,1971    ,331.8,333.9,334.1
XS GIS Cut Line= 4
2199090.06656254628267.1689874552199167.74317234 628381.04420123
2199270.16474297628714.4035808022199314.49199773628810.337763207
#Sta/Elev= 30
       0  2277.3    17.9 2272.44    32.1 2269.89   118.6 2257.37     138 2250.87
   142.2 2248.43   146.4 2245.45   154.7 2234.88   158.82231.263   167.1 2230.38
   184.72231.281   237.5 2233.58   276.1 2232.84   305.4 2237.12   317.9 2236.33
   326.3 2237.18   346.4 2237.29   359.8 2236.47   401.6 2236.28   435.1 2237.31
   443.5 2238.66   447.6 2239.56   452.6 2242.31   481.1 2266.52   485.3 2269.33
   498.5 2270.94   520.5 2271.66   524.9 2274.15   538.1 2284.75   592.3 2302.01
#Mann= 5 ,-1,0
       0      .1       0   158.8    .045       0   184.7      .1       0
  427.84     .06       0  536.58      .1       0
#XS Ineff= 2 , 0
                          237.83         2237.46
Permanent Ineff=
       F       F
Bank Sta=158.8,184.7
XS Rating Curve= 0 ,0
Exp/Cntr=0.3,0.1

Type RM Length L Ch R = 1 ,1637    ,212.5,206.8,200.1
XS GIS Cut Line= 4
2198932.91918669628458.6599659832198951.71164284628649.269164035
2199021.51219424628818.4012693482199068.04589517628874.778637785
#Sta/Elev= 30
       0 2265.17    14.6  2256.5    26.6 2250.75    38.7 2242.75    54.8 2234.11
    73.62221.699    74.9 2220.95    78.9 2220.83   102.42221.719   127.1 2224.31
   141.9 2223.95   155.3 2224.75   163.3 2224.39   171.3  2221.3   175.4 2220.74
   183.4 2220.82   200.1 2224.79   234.7 2241.22     239 2242.51     250 2244.11
     278 2245.97     291 2249.39   303.9 2249.46   317.4 2248.34   334.2 2249.59
   342.9 2251.53   369.5 2251.25   373.2 2252.09   383.3 2257.42   447.6  2275.2
#Mann= 5 ,-1,0
       0      .1       0    73.6    .045       0   102.4      .1       0
  311.53     .06       0   424.5      .1       0
#XS Ineff= 2 , 0
                        153.6911            2230
Permanent Ineff=
       F       F
Bank Sta=73.6,102.4
XS Rating Curve= 0 ,0
Exp/Cntr(USF)=0,0
Exp/Cntr=0.3,0.1

Type RM Length L Ch R = 1 ,1430    ,220.1,218.3,217
XS GIS Cut Line= 2
2198718.14825931628570.5198239942198947.23724852628926.681611902
#Sta/Elev= 30
       0 2255.04     3.7 2252.53    12.1 2248.51    17.4 2244.67    33.3 2231.62
    49.7  2215.6    53.72214.134    67.1 2213.19    74.92214.114      84 2218.99
    88.8 2220.06   122.1 2218.31   136.5 2220.21   153.9 2220.65   168.4 2217.18
   193.4 2214.57   217.2 2220.65     233 2220.97   245.7 2222.34   255.4 2226.22
   272.6 2237.37     287 2241.62   293.3 2242.34   326.6 2241.61   340.8 2249.12
   345.6 2250.58   373.9 2256.41   388.3 2260.68     397 2262.16   423.5 2270.29
#Mann= 4 ,-1,0
       0      .1       0    53.7    .045       0    74.9      .1       0
     340     .06       0
#XS Ineff= 1 ,-1
151.2557423.4773    2225
Permanent Ineff=
       F
Bank Sta=53.7,74.9
XS Rating Curve= 0 ,0
Exp/Cntr(USF)=0,0
Exp/Cntr=0.3,0.1

Type RM Length L Ch R = 1 ,1212    ,253.3,251.3,249.2
XS GIS Cut Line= 2
2198528.43394012628698.4875015592198811.21566118629003.641194214
#Sta/Elev= 30
       0 2251.16    11.4 2245.15      30 2231.89    40.8 2221.27    47.3 2212.19
    52.32207.815    58.3 2206.87    70.2 2207.76    76.1 2210.46      80 2210.98
    92.3 2209.47   106.4 2209.89   118.2 2207.68   129.1 2208.16   145.5 2210.12
   176.2 2210.76   182.9 2212.23   188.5 2215.61   205.4 2223.11   228.2 2225.84
   270.9 2225.58   281.9 2231.22   287.2 2233.24   311.5 2239.35   338.5 2245.06
   358.1  2250.8   376.3 2255.06   400.8 2263.26   409.3 2264.37     416 2266.61
#Mann= 6 ,-1,0
       0      .1       0    52.3    .045       0    70.2      .1       0
     210     .06       0     350      .1       0     360     .12       0
#XS Ineff= 2 , 0
                        80.40498            2215
Permanent Ineff=
       F       F
Bank Sta=52.3,70.2
XS Rating Curve= 0 ,0
Exp/Cntr(USF)=0,0
Exp/Cntr=0.3,0.1

Type RM Length L Ch R = 1 ,960     ,116.9,109.5,100
BEGIN DESCRIPTION:
Structure XS 4
END DESCRIPTION:
XS GIS Cut Line= 4
 2198318.3119038 628865.497212192198476.95229895628970.810335158
2198543.10741235628945.4985411832198693.08393796629075.770364862
#Sta/Elev= 30
       0 2237.26     9.8 2233.42    26.2 2221.11    35.8 2215.88    45.4 2212.02
    57.3 2208.96    73.3 2205.79   136.8 2206.02   141.5  2204.8   147.9 2199.83
   151.2 2198.79   164.9 2199.79   184.7 2202.86   202.4 2203.38   215.3 2204.84
   232.4 2202.92   245.3 2203.99   253.8 2202.05   262.7 2201.69     273 2204.22
   278.8 2208.27   283.9 2209.78   309.6 2210.21   321.3 2220.62     327 2223.75
   336.8 2227.19   389.8 2240.33   419.4 2246.45   443.8 2254.37   459.9 2257.63
#Mann= 6 ,-1,0
       0      .1       0   147.9    .045       0   164.9     .06       0
  250.41      .1       0  271.25     .06       0  421.25      .1       0
#XS Ineff= 2 , 0
                          262.47            2210
Permanent Ineff=
       F       F
Bank Sta=147.9,164.9
XS Rating Curve= 0 ,0
Exp/Cntr(USF)=0,0
Exp/Cntr=0.5,0.3

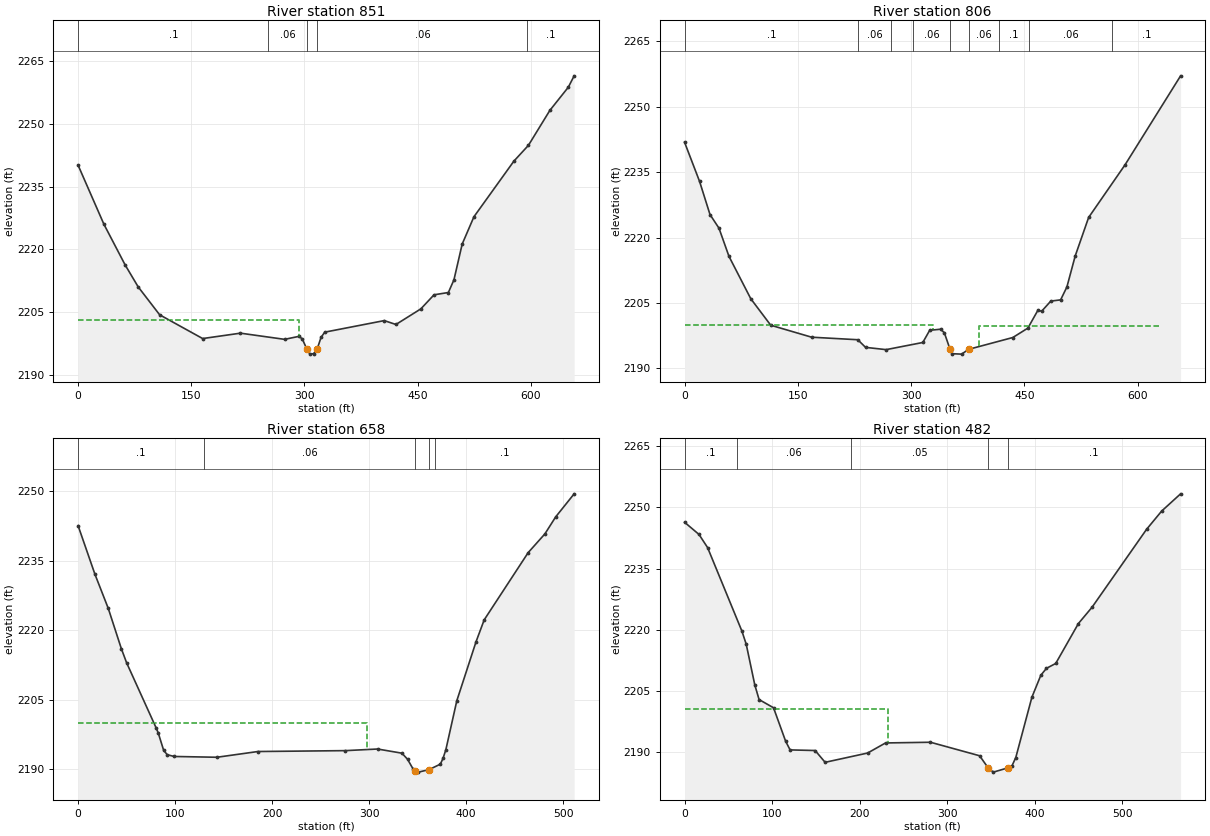
Type RM Length L Ch R = 1 ,851     ,44.8,44.9,40
BEGIN DESCRIPTION:
Structure XS 3
END DESCRIPTION:
XS GIS Cut Line= 6
2198207.87292214628949.9581332392198328.66873899629108.204149431
2198350.93807215629101.8052844352198408.23597906629070.086800252
2198551.48074634628964.6995786132198696.65639919629090.261667834
#Sta/Elev= 30
       0 2240.14    34.2 2226.01    62.4 2216.24    79.6 2211.01   108.1 2204.31
   165.1 2198.62   215.2 2199.91   273.7 2198.43   292.6 2199.14     297 2198.58
   303.1 2196.14   307.3 2194.89   312.2    2195     317 2196.16     317 2196.17
     322 2198.89   326.9 2200.15   405.8 2202.92   421.3 2201.99   454.3 2205.73
   471.8  2209.1   490.8 2209.65   498.2  2212.7   509.1 2221.25   524.7  2227.8
   577.6 2241.11   596.9  2244.9   625.3 2253.27   649.8 2258.83   657.5 2261.55
#Mann= 5 ,-1,0
       0      .1       0  252.25     .06       0   303.1    .045       0
     317     .06       0   595.6      .1       0
#XS Ineff= 2 , 0
          293.14 2203.02
Permanent Ineff=
       F       F
Bank Sta=303.1,317
XS Rating Curve= 0 ,0
Exp/Cntr(USF)=0,0
Exp/Cntr=0.5,0.3

Type RM Length L Ch R = 1 ,806     ,139.7,148.3,166.4
BEGIN DESCRIPTION:
Structure XS 2
END DESCRIPTION:
XS GIS Cut Line= 6
2198179.20096167628966.3280884682198323.96638039 629157.48573418
2198346.23571355629151.0868691842198403.53362046629119.368385001
2198546.77838774629013.981163362 2198660.9053335 629112.22039034
#Sta/Elev= 30
       0 2241.87    19.9 2232.88    33.7 2225.29    45.6 2222.16    58.8 2215.71
    87.7 2205.99   114.1 2199.92   168.3 2197.17   229.4 2196.59   239.7 2194.84
   266.9 2194.32   315.5 2195.96   324.6 2198.75     339    2199     344  2198.2
   351.62194.383   353.8 2193.39   366.8 2193.29   376.4  2194.4   434.7  2197.1
   454.6 2199.25   467.9 2203.34   472.9 2203.13     485 2205.45     498 2205.73
   506.3 2208.68   517.3 2215.79   535.1 2224.63   583.3 2236.69   656.9  2257.1
#Mann= 9 ,-1,0
       0      .1       0     230     .06       0  272.96      .1       0
  302.96     .06       0   351.6    .045       0   376.4     .06       0
  416.24      .1       0  456.24     .06       0  566.31      .1       0
#XS Ineff= 2 ,-1
       0  329.24    2200  390.54  630.612199.803
Permanent Ineff=
       F       F
Bank Sta=351.6,376.4
XS Rating Curve= 0 ,0
Exp/Cntr(USF)=0,0
Exp/Cntr=0.5,0.3

Type RM Length L Ch R = 1 ,658     ,177.7,176,175.2
BEGIN DESCRIPTION:
Structure XS 1
END DESCRIPTION:
XS GIS Cut Line= 4
2198079.09221638629052.4214645562198176.63401256629158.017170519
2198345.01963803 629201.763900562198481.42842774629338.957112569
#Sta/Elev= 30
       0 2242.55    17.4 2232.04    31.1 2224.69    44.6 2215.98      50 2212.95
    80.6 2198.81    82.7 2197.73    88.2 2194.03    91.9  2193.1      99 2192.72
   143.1 2192.55   185.3 2193.79   275.5 2193.98   308.6 2194.33   333.7 2193.43
   339.5 2192.12     345  2190.1   347.32189.638   350.7 2189.34   361.52189.867
   373.3 2191.06   376.1 2192.32     379 2194.19   390.3 2204.77   410.1 2217.49
   418.5 2222.22   463.8 2236.73   481.1 2240.79   492.1 2244.43   511.2 2249.43
#Mann= 5 ,-1,0
       0      .1       0     130     .06       0   347.3    .045       0
   361.5     .06       0  367.73      .1       0
#XS Ineff= 2 , 0
        298.0527    2200
Permanent Ineff=
       F       F
Bank Sta=347.3,361.5
XS Rating Curve= 0 ,0
Exp/Cntr(USF)=0,0
Exp/Cntr=0.3,0.1

Type RM Length L Ch R = 1 ,482     ,190.2,196.2,199.8
XS GIS Cut Line= 4
2197989.48437155629103.7192600862198059.08606098629202.045456264
2198293.30126985629389.8595388512198428.08549382629445.098974906
#Sta/Elev= 30
       0 2246.37    16.5 2243.37    26.3 2240.14    65.5 2219.61    70.4  2216.4
    80.2 2206.39    85.1  2202.8   101.6 2200.78   115.4 2192.57   120.5 2190.43
   149.1 2190.28   160.5 2187.38     209 2189.66   229.5 2192.14   280.8 2192.31
   336.9 2188.99   346.72185.995   352.6 2184.97   369.12186.013   373.9 2186.54
   378.2 2188.55   396.6 2203.38   406.8 2208.77   413.2 2210.47   423.8 2211.67
   449.7 2221.48   465.3 2225.49   527.5 2244.62   544.8 2249.12   566.4 2253.35
#Mann= 5 ,-1,0
       0      .1       0      60     .06       0  190.47     .05       0
   346.7    .045       0   369.1      .1       0
#XS Ineff= 2 , 0
          231.77 2200.59
Permanent Ineff=
       F       F
Bank Sta=346.7,369.1
XS Rating Curve= 0 ,0
Exp/Cntr(USF)=0,0
Exp/Cntr=0.3,0.1