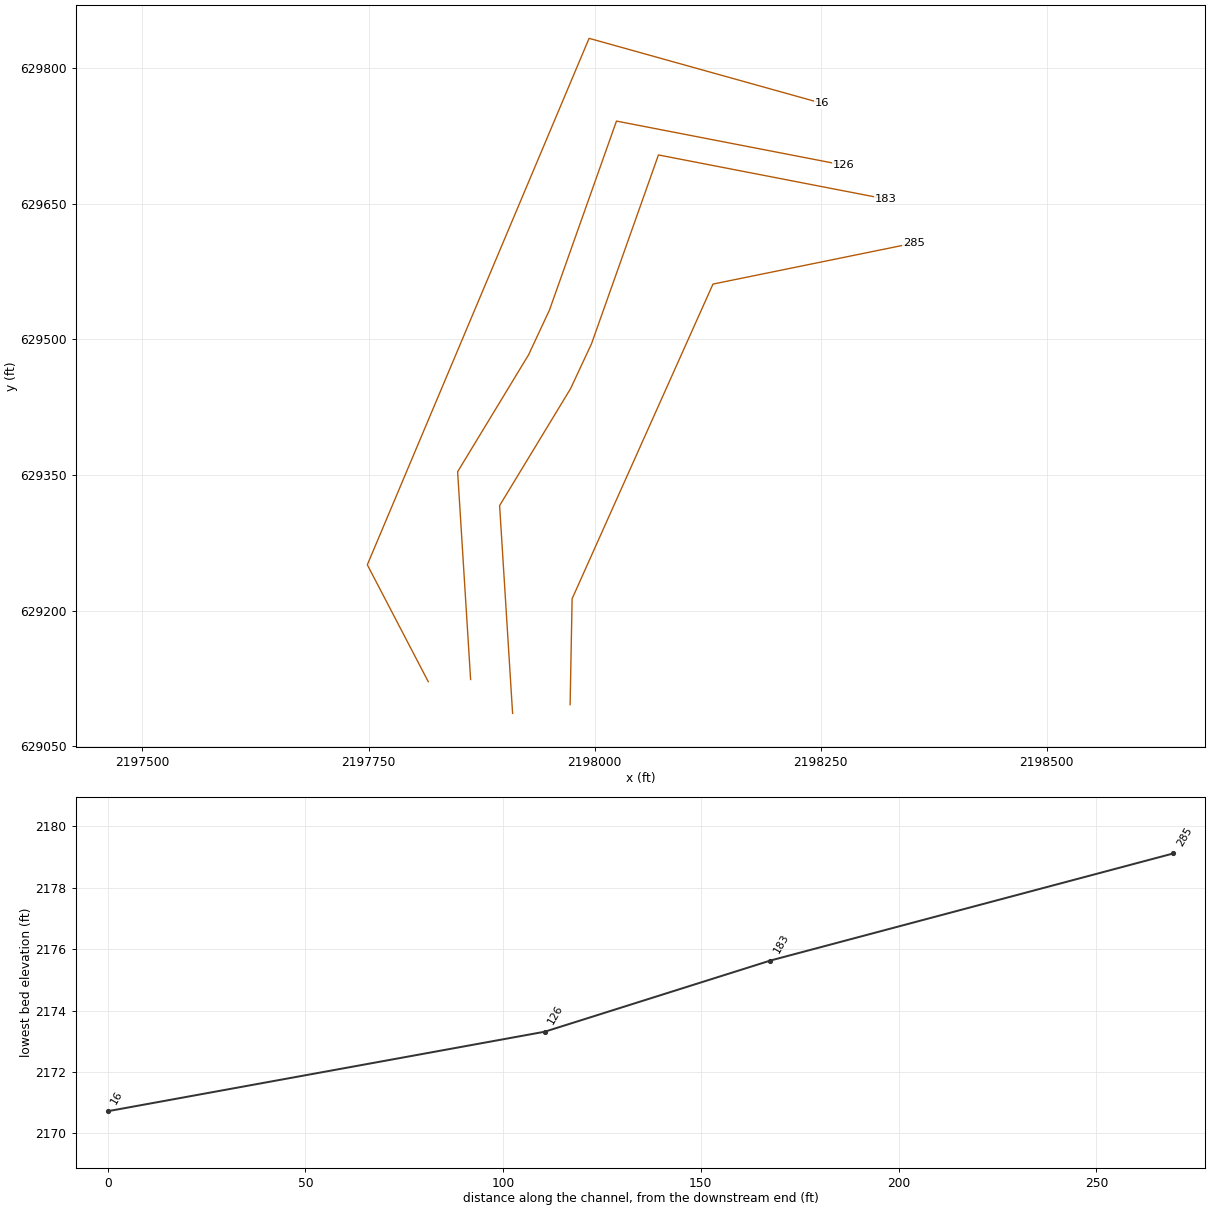
HEC-RAS study TROUTRN.prj: TROUTRN

--- TROUTRN.g01 (geometry) --- (continued)

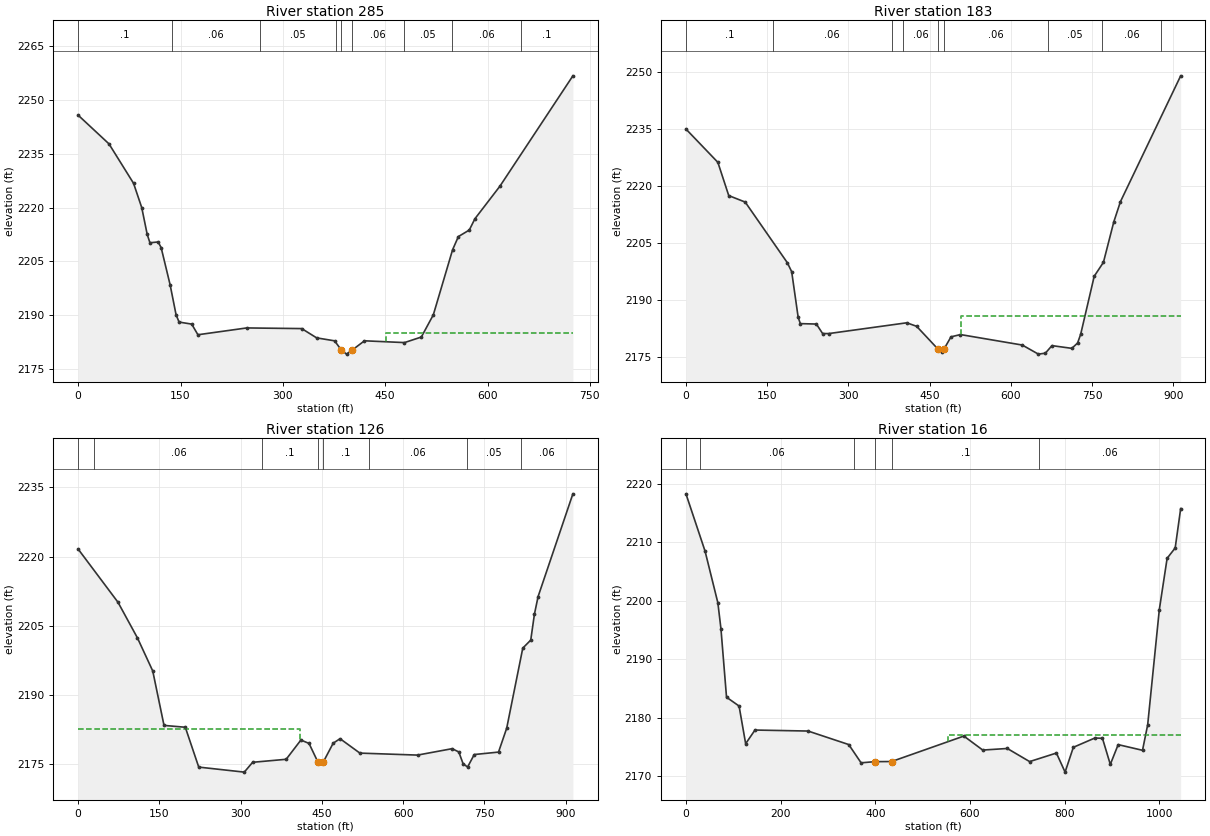
Type RM Length L Ch R = 1 ,285     ,102.1,101.9,101.9
XS GIS Cut Line= 4
2197972.91254073629095.9857390392197975.12211817629213.093343475
2198130.89732785629561.1017906212198352.95986079629606.398128186
#Sta/Elev= 30
       0 2245.82    45.2 2237.81    81.2  2226.8    93.2 2220.01   101.2 2212.53
   105.2 2210.21   117.2 2210.43   121.6 2208.87   134.8 2198.45   143.5  2190.1
   147.9 2188.07   166.4  2187.5   175.5 2184.53     247 2186.43   327.6 2186.25
   349.5 2183.66   375.8 2182.83   385.62180.282   393.3 2179.12   401.92180.301
   419.6 2182.84   478.2 2182.34   502.9 2183.89   520.5  2190.1   548.7 2208.25
   557.2 2211.94   573.2 2213.76   581.4  2216.9   618.1 2226.01     725 2256.81
#Mann= 9 ,-1,0
       0      .1       0  137.13     .06       0  267.13     .05       0
  377.13     .06       0   385.6    .045       0   401.9     .06       0
  477.13     .05       0  548.41     .06       0  648.41      .1       0
#XS Ineff= 2 , 0
                             451            2185
Permanent Ineff=
       F       F
Bank Sta=385.6,401.9
XS Rating Curve= 0 ,0
Exp/Cntr(USF)=0,0
Exp/Cntr=0.3,0.1

Type RM Length L Ch R = 1 ,183     ,56.9,57.1,56.8
XS GIS Cut Line= 6
2197909.30487443629086.3460168152197894.94262105629316.142070804
2197973.38262025629445.4023511732197996.58318339629495.117843622
2198070.60402771 629703.92291191 2198321.3910674629655.312208181
#Sta/Elev= 30
       0 2234.89    58.9 2226.13      79 2217.37   109.4 2215.66   187.2 2199.69
   195.2 2197.33   207.2  2185.3   211.2 2183.66   240.8 2183.55   252.3 2181.05
   263.5 2181.04   407.7 2183.88   425.9 2182.95     4652176.991   472.2 2176.17
   476.52176.991   489.3 2180.18   506.8 2180.78   620.9 2178.02   650.6 2175.63
   663.5 2175.88   675.7 2177.87   712.4 2177.15     723 2178.56   728.7 2180.86
   753.7 2196.14   770.7  2199.8   789.8 2210.43   802.1 2215.77   913.3  2248.9
#Mann= 9 ,-1,0
       0      .1       0     160     .06       0  380.24      .1       0
  401.44     .06       0     465    .045       0   476.5     .06       0
  667.85     .05       0  767.85     .06       0  877.85      .1       0
#XS Ineff= 2 , 0
                          506.86         2185.62
Permanent Ineff=
       F       F
Bank Sta=465,476.5
XS Rating Curve= 0 ,0
Exp/Cntr(USF)=0,0
Exp/Cntr=0.3,0.1

Type RM Length L Ch R = 1 ,126     ,123.3,110.5,101.2
XS GIS Cut Line= 6
2197862.87770399629123.7918926292197848.51545061629353.587946618
2197926.95544981629482.8482269872197950.15601295629532.563719436
2198024.17685727629741.3687877242198274.96389696629692.758083995
#Sta/Elev= 30
       0 2221.62    73.5 2210.11   109.5 2202.37   137.7 2195.22   158.5 2183.43
   197.8 2183.03   222.6  2174.4   306.7 2173.31   322.1 2175.44     384 2176.09
   411.2 2180.26   426.2 2179.53   442.5 2175.51   452.62175.519   470.8 2179.58
   483.5 2180.55   520.1 2177.43   626.5    2177   690.4 2178.39   702.7 2177.68
   710.8 2175.07     719 2174.43   731.2 2177.12     776 2177.65   791.1 2182.82
   820.8 2200.17   835.5 2201.91   842.3 2207.53   849.1 2211.35   913.3 2233.59
#Mann= 8 ,-1,0
       0      .1       0      30     .06       0  340.24      .1       0
   442.5    .045       0   452.6      .1       0  536.31     .06       0
  717.85     .05       0  817.85     .06       0
#XS Ineff= 2 , 0
          409.61 2182.67
Permanent Ineff=
       F       F
Bank Sta=442.5,452.6
XS Rating Curve= 0 ,0
Exp/Cntr(USF)=0,0
Exp/Cntr=0.3,0.1

Type RM Length L Ch R = 1 ,16      ,,,
XS GIS Cut Line= 4
2197816.03254234629121.3958796242197748.64043035629250.656159993
2197993.90352643629832.8798160122198251.31929845 629761.06854914
#Sta/Elev= 30
       0 2218.27    40.4 2208.47    67.4 2199.65    73.9 2195.24    85.7 2183.52
   112.2 2182.01   126.1 2175.58   145.8 2177.91   257.9 2177.74   343.8 2175.43
   369.9 2172.31   398.9 2172.51   434.4 2172.53   586.9 2176.88   626.8 2174.49
   678.7 2174.76   725.8 2172.52   782.4 2173.98   800.7 2170.72   818.1 2174.96
   863.6 2176.55   879.6  2176.5   896.2 2172.04   912.8 2175.42   964.2 2174.45
   975.1  2178.8   999.7 2198.49  1016.2 2207.26  1033.2 2209.02  1044.8 2215.75
#Mann= 6 ,-1,0
       0      .1       0      30     .06       0  355.77      .1       0
   398.9    .045       0   434.4      .1       0  745.77     .06       0
#XS Ineff= 1 ,-1
  553.871044.792    2177
Permanent Ineff=
       F
Bank Sta=398.9,434.4
XS Rating Curve= 0 ,0
Exp/Cntr(USF)=0,0
Exp/Cntr=0.3,0.1
LCMann Table=0

Chan Stop Cuts=-1
Use User Specified Reach Order=0
Composite Channel Slope=5